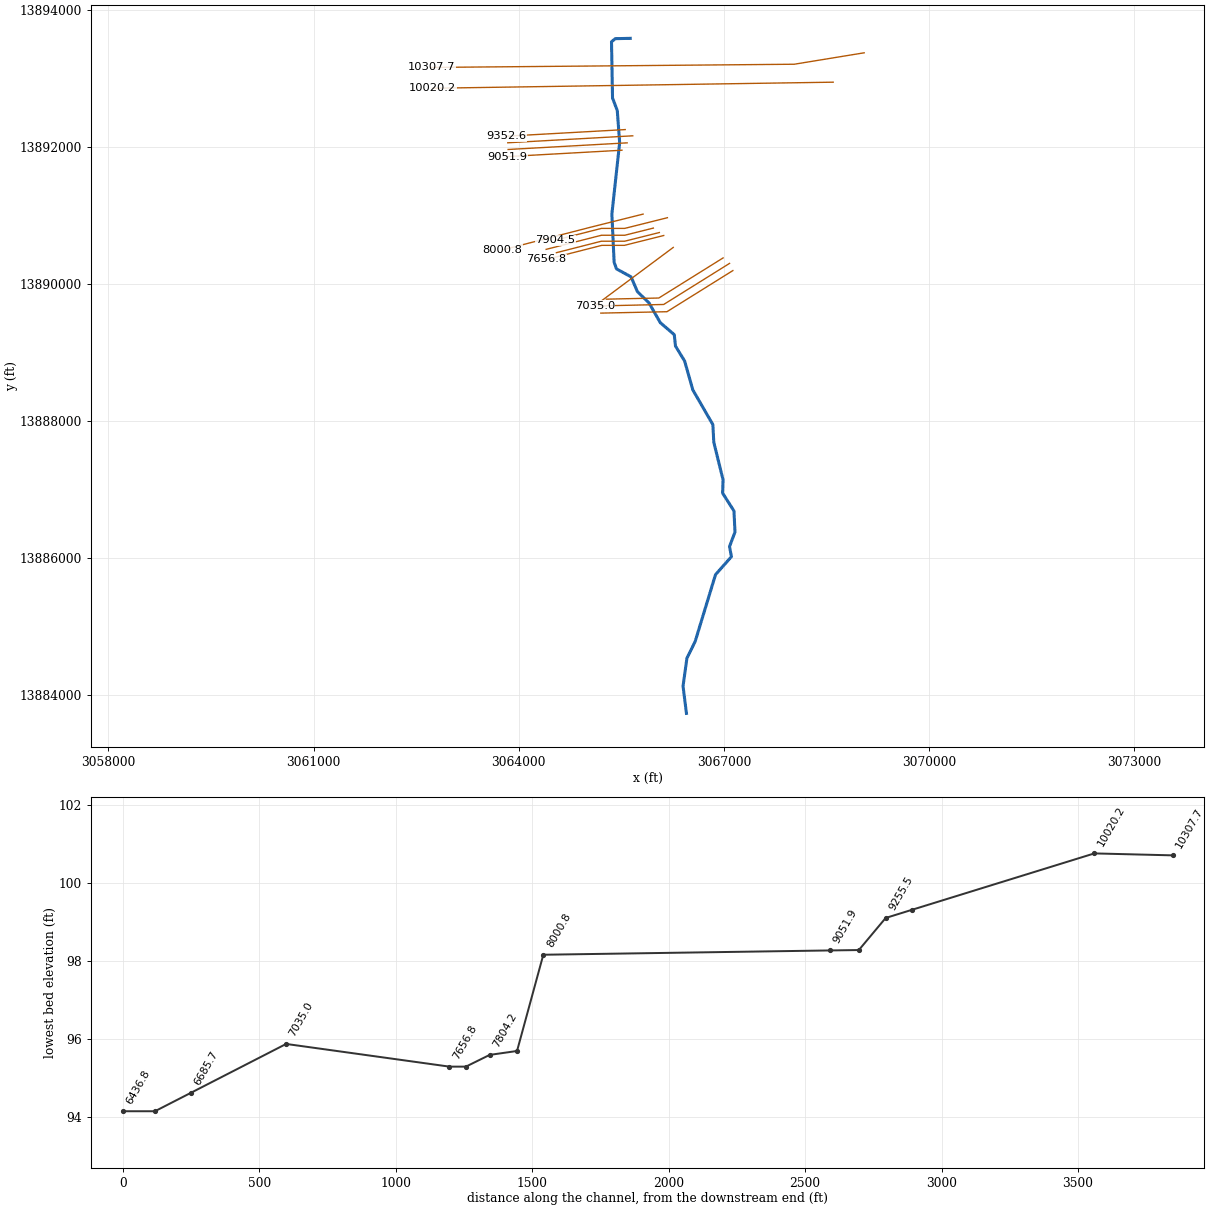
--- E125-00-00.prj (project) ---

Proj Title=E125-00-00
Current Plan=p01
Default Exp/Contr=.3,.1
English Units
Geom File=g01
Flow File=f02
Flow File=f01
Plan File=p02
Plan File=p01
Y Axis Title=Elevation
X Axis Title(PF)=Main Channel Distance
X Axis Title(XS)=Station
BEGIN DESCRIPTION:
HCFCD Watershed Unit ID: E
M3 Study Identifier: 2007_Effective_E
Engineer: HCFCD
Project Name: EffectiveFEMA Study for watershed White Oak Bayou (E)
Study Completion Date: 6/18/2007
FEMA Case Number: [No Data]
FEMA Approval Date: [No Date in Database]
Vertical Datum: NAVD 1988
Datum Note: 2001 ADJ
HYDRAULICS
HCFCD Unit No.:  E125-00-00
Hydraulic Program Name: HEC-RAS
Hydraulic Program Version: 3.0.1
Steady Hydraulic Model: Yes
Unsteady Hydraulic Model: No
Update1:
The effective FEMA hydraulic model for unit number E125-00-00 has been updated by FEMA LOMR 08-06-1925P with an effective date of 2/26/2009.
Update 2:
The effective FEMA hydraulic model for unit number E125-00-00 has been updated by FEMA LOMR 16-06-0575P with an effective date of 9/15/2014.
END DESCRIPTION:
DSS Export Rating Curves= 0
DSS Export Rating Curve Sorted= 0
DSS Export Volume Flow Curves= 0
DXF OffsetX= 0
DXF OffsetY= 0
DXF ScaleX= 1
DXF ScaleY= 10

--- E125-00-00.p01 (plan) ---

Plan Title=FEMA Effective Multi-Profile 2014
Version=Version 3.0.1  May 2012
Short Identifier=Eff+LOMR MP
Geom File=g01
Flow File=f01
Subcritical Flow
K Sum by GR= 0
Std Step Tol= 0.01
Critical Tol= 0.01
Num of Std Step Trials= 20
Max Error Tol= 0.3
Flow Tol Ratio= 0.001
Split Flow NTrial= 30
Split Flow Tol= 0.02
Split Flow Ratio= 0.02
Log Output Level= 0
Friction Slope Method= 1
Unsteady Friction Slope Method= 2
Parabolic Critical Depth
Global Vel Dist= 0 , 0 , 0
Global Log Level= 0
CheckData=True
Encroach Param=-1 ,0,0, 0
BEGIN DESCRIPTION:
FEMA Effective June 2007 + LOMR 08-06-1925P + LOMR 14-06-0575P
END DESCRIPTION:
Computation Interval=1HOUR
Output Interval=1HOUR
Run HTab= 0
Run UNet= 0
Run PostProcess= 0
UNET Theta= 1
UNET ZTol= 0.02
UNET ZSATol= 0.1
UNET MxIter= 20
UNET MaxInSteps= 20
UNET DtIC= 0
UNET DtMin= 0
UNET MaxCRTS= 20
UNET WFStab= 2
UNET SFStab= 1
UNET WFX= 1
UNET SFX= 1
UNET Convert EG Bridges=-1
UNET Use Existing IB Tables=-1
Instantaneous Interval=1HOUR
Write IC File= 0
Write Velocity= 0
Write Detailed= 0

--- E125-00-00.p02 (plan) ---

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Plan Title=FEMA Effective Floodway 2014
Short Identifier=Eff+LOMR FW
Geom File=g01
Flow File=f02
Encroach Param=-1 ,0,0, 2
Encroach River=E125-00-00
Encroach Reach=E125-00-00_0002
Encroach Node=10307.7
       1 4924.96 5193.05
Encroach Node=10020.2
       1 4914.05 5145.83
Encroach Node=9352.6
       1 4973.98 5450.76
Encroach Node=9255.5
       1  4982.7 5495.11
Encroach Node=9205.5
       1  4982.7 5495.11
Encroach Node=9157.2
       1  4982.7 5495.11
Encroach Node=9051.9
       1 4982.29 5473.85
Encroach Node=8000.8
       1  4978.2  5261.6
Encroach Node=7904.5
       1 4970.73 5250.97
Encroach Node=7804.2
       1 4970.73 5242.12
Encroach Node=7717.1
       1 4970.76 5226.03
Encroach Node=7684.8
       1  4968.1    5211
Encroach Node=7656.8
       1  4968.1    5211
Encroach Node=7035.0
       1    4963    5043
Encroach Node=6685.7
       1 4943.39 5039.37
Encroach Node=6554.2
       1    4936    5038
Encroach Node=6507.6
       1    4936    5038
Encroach Node=6436.8
       1    4936    5038
Encroach Node=6326.3
       1 4947.27 5025.56
Encroach Node=5648.8
       1    4960    5040
Encroach Node=5225.3
       1 4960.24 5040.79
Encroach Node=5125.3
       1    4938    5068
Encroach Node=5114.9
       1    4938    5068
Encroach Node=5088.7
       1    4938    5068
Encroach Node=4988.7
       1  4936.4 5060.23
Encroach Node=4611.6
       1  4949.1  5046.4
Encroach Node=4003.7
       1  4958.8  5025.7
Encroach Node=3042.8
       1  4951.5  5051.5
Encroach Node=2943.8
       1  4952.1  5044.9
Encroach Node=2915.8
       1  4952.1  5044.9
Encroach Node=2887.8
       1  4952.1  5044.9
Encroach Node=2781.2
       1 4955.55 5046.42
Encroach Node=2535.1
       1  4963.5  5071.1
Encroach Node=1507.6
       1  4971.6  5024.4
Encroach Node=1100.5
       1  4977.3  5021.3
Encroach Node=558.7
       1 4939.61 5042.87
Encroach Node=460.8
       1  4932.8  5059.6
Encroach Node=434.3
       1  4932.8  5059.6
Encroach Node=407.8
       1  4932.8  5059.6
Encroach Node=299.1
       1  4953.5  5043.5
Encroach Node=154.1
       1  4977.3  5021.3
FEMA Effective FLoodway June 2007 + LOMR 08-06-1925P + LOMR 14-06-0575P

--- E125-00-00.f01 (steady flow) ---

Flow Title=FEMA Effective June 2007
Version=Version 3.0.1  Mar 2001
Number of Profiles= 4
Profile Names=10PCT_10yr, 2PCT_50yr, 1PCT_100yr, 0.2PCT_500yr
River Rch & RM=E125-00-00,E125-00-00_0002       ,10307.7
     470     720     840    1300
River Rch & RM=E125-00-00,E125-00-00_0002       ,10020.2
     490     750     890    1360
River Rch & RM=E125-00-00,E125-00-00_0002       ,9255.5
     540     820     980    1470
River Rch & RM=E125-00-00,E125-00-00_0002       ,8000.8
     570     860    1060    1560
River Rch & RM=E125-00-00,E125-00-00_0002       ,7035.0
     590     890    1100    1600
River Rch & RM=E125-00-00,E125-00-00_0002       ,6554.2
     620     940    1150    1650
River Rch & RM=E125-00-00,E125-00-00_0002       ,5648.8
     650    1000    1200    1710
River Rch & RM=E125-00-00,E125-00-00_0002       ,4611.6
     670    1030    1240    1740
River Rch & RM=E125-00-00,E125-00-00_0002       ,4003.7
     700    1100    1300    1800
River Rch & RM=E125-00-00,E125-00-00_0002       ,2943.8
     740    1140    1350    1900
River Rch & RM=E125-00-00,E125-00-00_0002       ,1507.6
     784    1187    1392    1997
Boundary for River Rch & Prof#=E125-00-00,E125-00-00_0002       , 1
Up Type= 0
Dn Type= 3
Dn Slope=.0017
Boundary for River Rch & Prof#=E125-00-00,E125-00-00_0002       , 2
Up Type= 0
Dn Type= 3
Dn Slope=.0017
Boundary for River Rch & Prof#=E125-00-00,E125-00-00_0002       , 3
Up Type= 0
Dn Type= 3
Dn Slope=.0017
Boundary for River Rch & Prof#=E125-00-00,E125-00-00_0002       , 4
Up Type= 0
Dn Type= 3
Dn Slope=.0017
DSS Import GetInterval= 0
DSS Import GetPeak= 0
DSS Import FillOption= 0

--- E125-00-00.f02 (steady flow) ---

Flow Title=Floodway
Version=Version 3.0.1  Mar 2001
Number of Profiles= 2
Profile Names=1PCT_100yr, 1PCTFloodway_100yrFW
River Rch & RM=E125-00-00,E125-00-00_0002       ,10307.7
     840     840
River Rch & RM=E125-00-00,E125-00-00_0002       ,10020.2
     890     890
River Rch & RM=E125-00-00,E125-00-00_0002       ,9255.5
     980     980
River Rch & RM=E125-00-00,E125-00-00_0002       ,8000.8
    1060    1060
River Rch & RM=E125-00-00,E125-00-00_0002       ,7035.0
    1100    1100
River Rch & RM=E125-00-00,E125-00-00_0002       ,6554.2
    1150    1150
River Rch & RM=E125-00-00,E125-00-00_0002       ,5648.8
    1200    1200
River Rch & RM=E125-00-00,E125-00-00_0002       ,4611.6
    1240    1240
River Rch & RM=E125-00-00,E125-00-00_0002       ,4003.7
    1300    1300
River Rch & RM=E125-00-00,E125-00-00_0002       ,2943.8
    1350    1350
River Rch & RM=E125-00-00,E125-00-00_0002       ,1507.6
    1392    1392
Boundary for River Rch & Prof#=E125-00-00,E125-00-00_0002       , 1
Up Type= 0
Dn Type= 3
Dn Slope=.0017
Boundary for River Rch & Prof#=E125-00-00,E125-00-00_0002       , 2
Up Type= 0
Dn Type= 1
Dn Known WS=90.53
DSS Import GetInterval= 0
DSS Import GetPeak= 0
DSS Import FillOption= 0

--- E125-00-00.g01 (geometry) ---

Geom Title=E125-00-00
Version=Version 3.0.1  May 2012

River Reach=E125-00-00      ,E125-00-00_0002
Reach XY= 30
       3065631.5       13893591.      3065411.25       13893586.
       3065356.5       13893541.      3065371.46     13892719.81
      3065440.91     13892536.65      3065475.63      13892067.9
      3065361.91      13891024.5       3065394.9     13890321.37
      3065429.62     13890224.15       3065642.3      13890108.7
      3065736.05     13889890.81      3065906.18     13889726.75
      3066070.24     13889439.02      3066274.23     13889264.54
      3066292.46       13889097.      3066426.14     13888879.12
      3066545.93     13888457.25      3066838.83     13887950.98
      3066852.36     13887693.36      3066987.77     13887145.62
      3066980.83     13886951.17       3067147.5     13886689.89
      3067162.25     13886381.73      3067082.39     13886170.79
      3067110.47     13886022.56      3066877.53      13885760.2
      3066579.79     13884783.64      3066459.13     13884539.71
       3066402.7     13884130.86      3066452.54      13883734.4

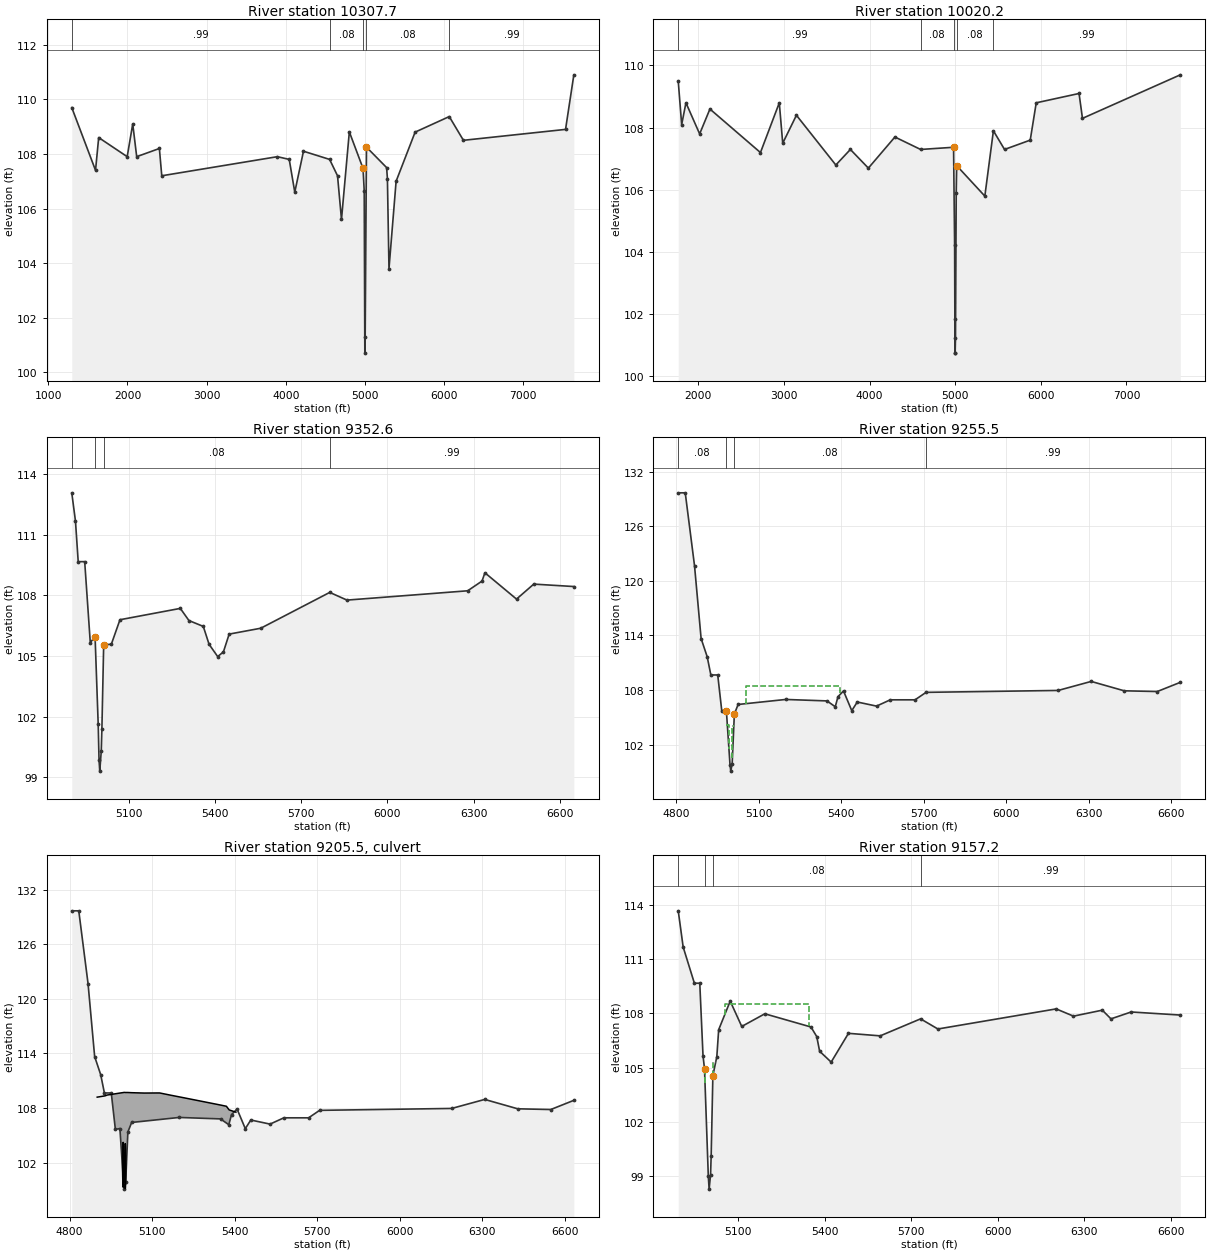
Type RM Length L Ch R = 1 ,10307.7 ,287.3,287.5,290
BEGIN DESCRIPTION:
Cross Section Xsec10; Low point on right is drainage ditch from road VRR
Located At: PRAIRIE DR
END DESCRIPTION:
XS GIS Cut Line= 3
      3069051.79     13893379.83      3068028.76      13893212.8
      3062724.16     13893166.17
#Sta/Elev= 30
  1296.2   109.7  1596.2   107.4  1636.2   108.6  1996.2   107.9  2066.2   109.1
  2116.2   107.9  2402.8   108.2  2432.8   107.2  3892.8   107.9  4042.8   107.8
  4112.8   106.6  4222.8   108.1  4552.8   107.8  4652.8   107.2  4702.8   105.6
  4801.9  108.81    4975  107.47  4989.9  106.65  4997.7   100.7    5002  101.28
  5018.5  108.25  5272.8   107.5  5282.8   107.1  5302.8   103.8  5392.8     107
  5632.8   108.8    6064  109.37  6242.8   108.5  7532.8   108.9  7637.6   110.9
#Mann= 5 ,-1 , 0
  1296.2     .99       0  4552.8     .08       0    4975     .04       0
  5018.5     .08       0    6064     .99       0
Bank Sta=4975,5018.5
XS Rating Curve= 0
Exp/Cntr=.3,.1

Type RM Length L Ch R = 1 ,10020.2 ,663.9,667.6,659.6
BEGIN DESCRIPTION:
Cross Section Xsec9.0
Located At: DS PRAIRIE
END DESCRIPTION:
XS GIS Cut Line= 2
 3068598.714238813892950.7676627        3062737.      13892862.2
#Sta/Elev= 30
  1766.1   109.5  1806.1   108.1  1856.1   108.8  2016.1   107.8  2136.1   108.6
  2726.1   107.2  2946.1   108.8  2986.1   107.5  3146.1   108.4  3606.1   106.8
  3776.1   107.3  3986.1   106.7  4296.1   107.7  4596.1   107.3    4981  107.37
  4993.3  104.22  4996.2  101.86  4996.6  100.76  4999.5  100.75  5003.5  101.24
    5012  105.89  5017.4  106.78  5346.1   105.8  5446.1   107.9  5576.1   107.3
  5876.1   107.6  5946.1   108.8  6446.1   109.1  6486.1   108.3  7628.5   109.7
#Mann= 5 ,-1 , 0
  1766.1     .99       0  4596.1     .08       0    4981     .04       0
  5017.4     .08       0  5446.1     .99       0
Bank Sta=4981,5017.4
XS Rating Curve= 0
Exp/Cntr=.3,.1

Type RM Length L Ch R = 1 ,9352.6  ,97,97.1,97
XS GIS Cut Line= 2
 3065556.801988413892258.6818604      3063812.26     13892161.55
#Sta/Elev= 30
 4901.38  113.06 4914.27  111.66 4923.78  109.66 4946.35  109.66 4965.81  105.66
 4982.48  105.96 4993.33  101.63 4996.24   99.87  4998.8   99.31 5004.04  100.31
 5006.24  101.41 5012.42  105.55  5039.1  105.58  5069.1  106.79  5279.1  107.35
  5309.1  106.75  5359.1  106.46  5379.1  105.58  5409.1  104.97  5429.1   105.2
  5449.1  106.08  5559.1  106.37  5799.1  108.14  5859.1  107.76  6279.1  108.22
  6329.1   108.7  6339.1  109.11  6449.1  107.81  6509.1  108.55  6648.6  108.43
#Mann= 4 ,-1 , 0
 4901.38     .08       0 4982.48     .04       0 5012.42     .08       0
  5799.1     .99       0
Bank Sta=4982.48,5012.42
XS Rating Curve= 0
Exp/Cntr=.5,.3

Type RM Length L Ch R = 1 ,9255.5  ,99.1,98.3,98.3
BEGIN DESCRIPTION:
Access Road DS Prairie - 3
END DESCRIPTION:
XS GIS Cut Line= 3
  3065666.92367813892167.7906789      3065656.32      13892167.2
      3063839.61       13892066.
#Sta/Elev= 30
 4807.78  129.66 4833.23  129.66 4866.95  121.66  4890.9  113.66 4912.97  111.66
 4926.33  109.66 4951.28  109.66 4966.21  105.66  4982.7  105.75  4995.9   99.81
  4998.7    99.1  5003.7   99.89  5011.7  105.37  5025.4  106.42  5198.4  106.97
  5348.4  106.81  5378.4  106.17  5388.4  107.28  5408.4   107.9  5438.4  105.74
  5458.4  106.69  5528.4  106.24  5578.4  106.93  5668.4  106.93  5708.4  107.75
  6188.4  107.96  6308.4  108.95  6428.4  107.92  6548.4  107.84  6632.3  108.85
#Mann= 4 ,-1 , 0
 4807.78     .08       0  4982.7     .04       0  5011.7     .08       0
  5708.4     .99       0
#XS Ineff= 4 ,-1
    4900 4940.13   109.2 4986.42 4992.18   104.2 5004.58 5009.95   104.1
 5054.19 5394.95  108.47
Permanent Ineff=
       F       F       F       F
#Block Obstruct= 2 , 0
       0    4857   108.7               0
Bank Sta=4982.7,5011.7
XS Rating Curve= 0
Exp/Cntr=.5,.3

Type RM Length L Ch R = 2 ,9205.5  ,,,
BEGIN DESCRIPTION:
ACCESS ROAD DS PRAIRIE; Landfill
Structure ID: E125-00-00-05
END DESCRIPTION:
Bridge Culvert--1,0,-1,-1, 0
Deck Dist Width WeirC Skew NumUp NumDn MinLoCord MaxHiCord MaxSubmerge Is_Ogee
10,79,2.6,0, 23, 26, , , .95, 0, ,,,
  4900.2  4928.5  4936.3  4942.8  4982.7  4994.2  4995.9  4998.2  4998.7  5003.7
  5005.8  5011.7  5025.4    5071  5071.3  5116.7  5127.2  5168.1  5217.2  5347.2
  5369.7  5379.7  5404.3
   109.2  109.34  109.43  109.46  109.65   109.7  109.71  109.72  109.72  109.71
  109.71  109.71  109.69  109.65  109.65  109.66  109.66  109.41  109.12  108.34
   108.2   107.8  107.55
                                                                                
                                                                                
                        
 4872.37  4900.2  4928.5  4936.3  4942.8  4982.7  4994.2  4995.9  4998.2  4998.7
  5003.7  5005.8  5011.7  5025.4    5071  5071.3  5116.7  5127.2  5168.1  5217.2
  5347.2  5369.7  5379.7  5404.3    5430    5450
 109.175   109.2  109.34  109.43  109.46  109.65   109.7  109.71  109.72  109.72
  109.71  109.71  109.71  109.69  109.65  109.65  109.66  109.66  109.41  109.12
  108.34   108.2   107.8  107.55     106     106
                                                                                
                                                                                
                                                
BR Coef= 1 , 0 , 0 ,1.25, 0 ,,,.8,-1,2,0,
WSPro=,,,, 1 ,,,, 0 ,,,, 0 ,,,,-1 ,-1 ,-1 , 0 , 0 , 0 , 0 , 0
Culvert=1,5,,79,.015,.2,1,1,3,99.28,4994.7,99.11,4994.7,Culvert #1  , 0 ,10
Culvert Bottom n=.015
Culvert=1,5,,79,.02,.2,1,1,3,99.12,5002.1,98.75,5002.1,Culvert #2  , 0 ,10
Culvert Bottom n=.02
BC Design=,, 0 ,, 0 ,,,,,,
BC HTab HWMax=111.91

Type RM Length L Ch R = 1 ,9157.2  ,104.8,105.3,103.6
BEGIN DESCRIPTION:
Access Road DS Prairie - 2
END DESCRIPTION:
XS GIS Cut Line= 2
 3065585.634059313892064.9506715       3063844.4       13891968.
#Sta/Elev= 30
 4891.62  113.66  4908.7  111.66  4947.6  109.66  4966.3  109.66  4977.5  105.66
  4982.7  104.93  4995.9   98.99  4998.7   98.28  5003.7   99.07  5005.8  100.13
  5011.7  104.55  5025.4   105.6  5031.8  107.09  5071.8  108.67  5111.8  107.27
  5191.8  107.97  5351.8  107.24  5371.8  106.71  5381.8   105.9  5421.8   105.3
  5481.8  106.89  5591.8  106.75  5731.8  107.69  5791.8  107.13  6201.8  108.24
  6261.8  107.84  6361.8  108.17  6391.8  107.69  6461.8  108.07  6632.2   107.9
#Mann= 4 ,-1 , 0
 4891.62      .1       0  4982.7     .04       0  5011.7     .08       0
  5731.8     .99       0
#XS Ineff= 4 ,-1
 4871.51 4940.71  109.24  4982.7 4984.59  104.93  5011.8 5021.43   105.3
  5052.1 5345.21   108.5
Permanent Ineff=
       F       F       F       F
#Block Obstruct= 2 , 0
       0  4849.2   108.7               0
Bank Sta=4982.7,5011.7
XS Rating Curve= 0
Exp/Cntr=.5,.3

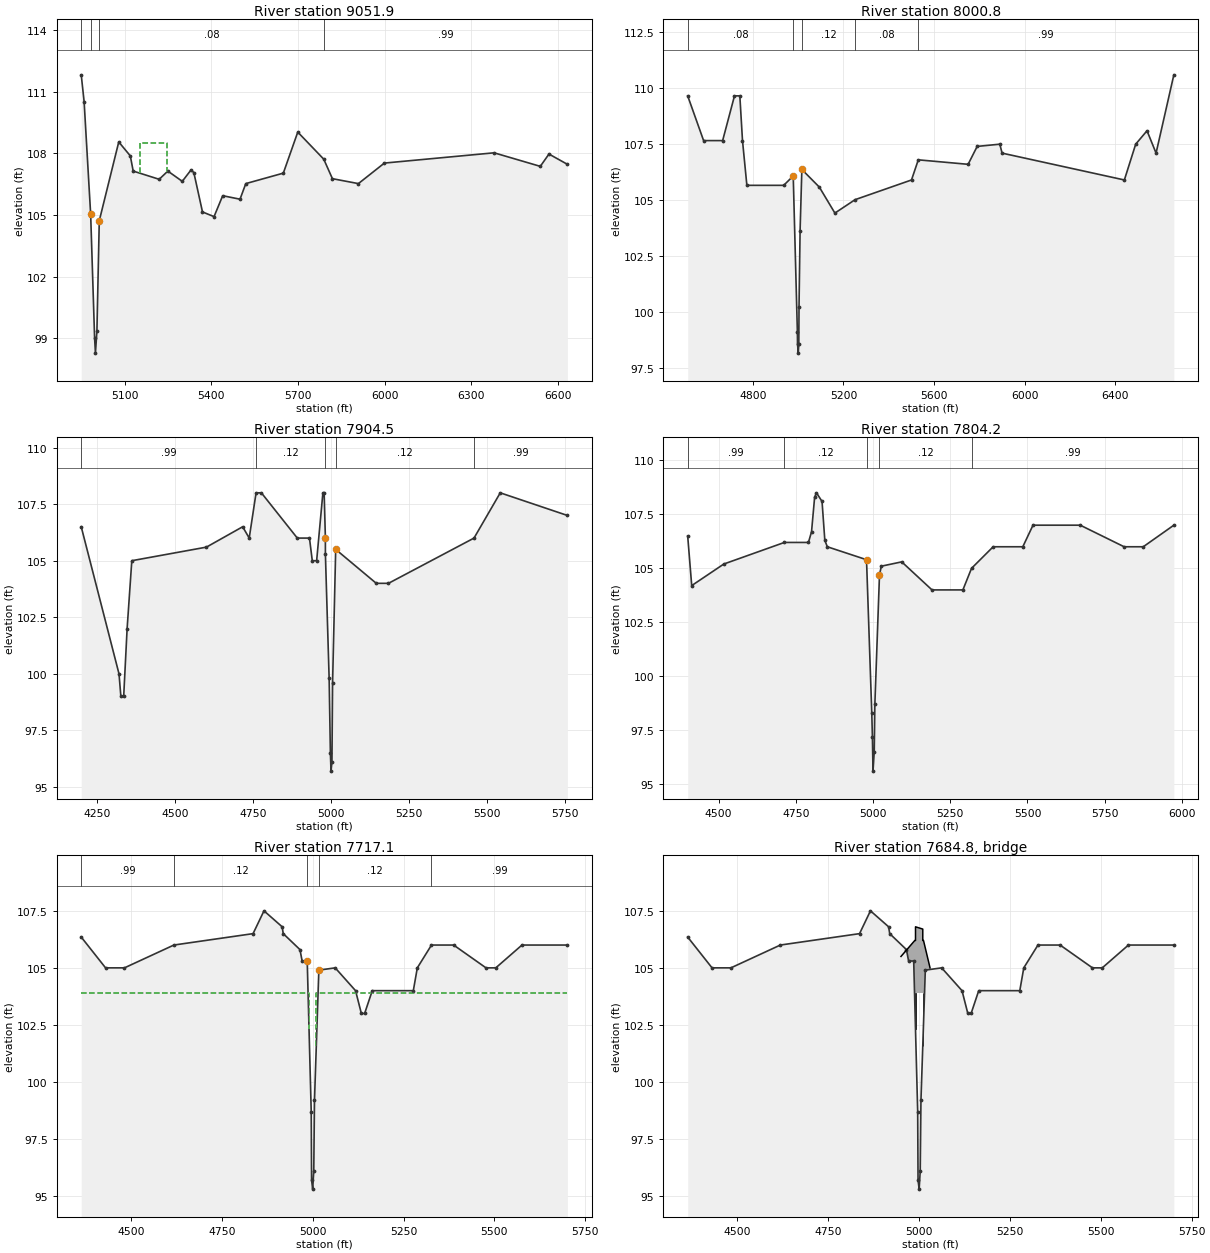
Type RM Length L Ch R = 1 ,9051.9  ,1027.4,1051.1,1106.3
BEGIN DESCRIPTION:
Access Road DS Prairie - 1
Interpolated channel, LIDAR overbanks
Spills into E141-00-00
END DESCRIPTION:
XS GIS Cut Line= 2
  3065509.327196 13891957.409465      3063828.17     13891863.85
#Sta/Elev= 30
  4949.6  111.83  4959.6  110.53 4982.29  105.03 4995.96      99 4998.85   98.27
 5003.96   99.35 5012.12  104.72  5079.6  108.56  5119.6  107.88  5129.6  107.14
  5219.6  106.74  5249.6  107.14  5299.6  106.64  5329.6  107.19  5339.6  107.07
  5369.6  105.15  5409.6  104.92  5439.6  105.94  5499.6  105.77  5519.6  106.53
  5649.6  107.04  5699.6  109.04  5789.6  107.72  5819.6  106.77  5909.6  106.53
  5999.6  107.53  6379.6  108.03  6539.6  107.37  6569.6  107.97  6633.4  107.47
#Mann= 4 ,-1 , 0
  4949.6      .1       0 4982.29     .04       0 5012.12     .08       0
  5789.6     .99       0
#XS Ineff= 1 ,-1
  5152.1 5245.21   108.5
Permanent Ineff=
       F
Bank Sta=4982.29,5012.12
XS Rating Curve= 0
Exp/Cntr=.3,.1

Type RM Length L Ch R = 1 ,8000.8  ,101.1,96.3,55.2
BEGIN DESCRIPTION:
Cross Section Xsec8.0
Located At: 2ND US RODNEY RAY BLVD
END DESCRIPTION:
XS GIS Cut Line= 3
 3065818.649253413891024.5710431      3065052.04     13890833.24
      3063755.63     13890500.04
#Sta/Elev= 30
 4512.17  109.66 4582.44  107.66 4666.51  107.66 4718.83  109.66 4742.43  109.66
 4754.19  107.66 4773.51  105.66 4936.11  105.66  4978.2  106.08  4996.6   99.09
  4997.1   98.59  5000.4   98.16  5002.9   98.58  5003.8  100.23  5008.5  103.63
  5016.3  106.37  5093.6  105.58  5162.2  104.42  5251.5  105.02  5500.5   105.9
  5530.5   106.8  5750.5   106.6  5790.5   107.4  5890.5   107.5  5900.5   107.1
  6440.5   105.9  6490.5   107.5  6540.5   108.1  6580.5   107.1    6659   110.6
#Mann= 5 ,-1 , 0
 4512.17     .08       0  4978.2     .04       0  5016.3     .12       0
  5251.5     .08       0  5530.5     .99       0
Bank Sta=4978.2,5016.3
XS Rating Curve= 0
Exp/Cntr=.3,.1

Type RM Length L Ch R = 1 ,7904.5  ,100.4,100.3,97.3
BEGIN DESCRIPTION:
Added Case No. 08-06-1925P
END DESCRIPTION:
XS GIS Cut Line= 5
 3066174.475746913890971.9527926      3066057.09      13890942.6
       3065549.2      13890815.6      3065209.26      13890815.6
 3064536.211839613890644.2420316
#Sta/Elev= 30
    4200   106.5    4321     100    4327      99    4336      99    4347     102
    4362     105    4601   105.6    4717   106.5    4738     106    4760     108
    4777     108    4892     106    4931     106    4940     105    4954     105
    4974     108    4978     108    4982     106    4982   105.3    4994    99.8
    4998    96.5    5000    95.7    5003    96.1    5005    99.6    5015   105.5
    5145     104    5184     104    5458     106    5542     108    5757     107
#Mann= 5 ,-1 , 0
    4200     .99       0    4760     .12       0    4982     .04       0
    5015     .12       0    5458     .99       0
Bank Sta=4982,5015
XS Rating Curve= 0
Exp/Cntr=.3,.1

Type RM Length L Ch R = 1 ,7804.2  ,87.1,87.1,84.3
BEGIN DESCRIPTION:
Added Case No. 08-06-1925P
END DESCRIPTION:
XS GIS Cut Line= 5
 3065968.808157313890820.5247592 3065956.196465513890817.3711534
       3065549.2      13890715.6      3065209.26      13890715.6
       3064400.5      13890509.7
#Sta/Elev= 30
    4400   106.5    4413   104.2    4517   105.2    4713   106.2    4791   106.2
    4801   106.7    4811   108.3    4817   108.5    4835   108.1    4844   106.3
    4852     106    4979   105.4    4996    98.3    4998    97.2    5000    95.6
    5004    96.5    5006    98.7    5021   104.7    5027   105.1    5093   105.3
    5191     104    5291     104    5319     105    5389     106    5485     106
    5518     107    5671     107    5813     106    5875     106    5974     107
#Mann= 5 ,-1 , 0
    4400     .99       0    4713     .12       0    4979     .04       0
    5021     .12       0    5319     .99       0
Bank Sta=4979,5021
XS Rating Curve= 0
Exp/Cntr=.3,.1

Type RM Length L Ch R = 1 ,7717.1  ,60.4,60.3,60.2
BEGIN DESCRIPTION:
Added Case No. 08-06-1925P
END DESCRIPTION:
XS GIS Cut Line= 4
       3066056.2      13890755.6       3065548.3      13890628.6
      3065208.36      13890628.6 3064550.817192713890461.1896923
#Sta/Elev= 30
    4363  106.35    4430     105    4482     105    4618     106    4836   106.5
    4866   107.5    4916   106.8    4919   106.5    4965   105.8    4971   105.3
    4985   105.3    4996    98.7    4997    95.7    5000    95.3    5003    96.1
    5005    99.2    5017   104.9    5062     105    5118     104    5134     103
    5143     103    5164     104    5277     104    5288     105    5327     106
    5388     106    5477     105    5504     105    5576     106    5701     106
#Mann= 5 ,-1 , 0
    4363     .99       0    4618     .12       0    4985     .04       0
    5017     .12       0    5327     .99       0
#XS Ineff= 2 , 0
       0    4990   103.9    5010       0   103.9
Permanent Ineff=
       F       F
Bank Sta=4985,5017
XS Rating Curve= 0
Exp/Cntr=.3,.1

Type RM Length L Ch R = 3 ,7684.8  ,,,
BEGIN DESCRIPTION:
Added Case No. 08-06-1925P
END DESCRIPTION:
Bridge Culvert--1,0,-1,-1, 0
Deck Dist Width WeirC Skew NumUp NumDn MinLoCord MaxHiCord MaxSubmerge Is_Ogee
20,25,2.6,0, 10, 10, , , .95, 0, 0,0,,
    4950    4988    4988    4990    4990    5010    5010    5012    5012    5030
   105.5   106.2   106.2   106.2   106.8   106.7   106.2   106.2   106.2     105
     100     100   103.9   103.9   103.9   103.9   103.9   103.9     100     100
    4960    4988    4988    4990    4990    5010    5010    5012    5012    5030
   105.5   106.2   106.2   106.2   106.7   106.8   106.2   106.2   106.2     105
     100     100   103.9   103.9   103.9   103.9   103.9   103.9     100     100
Pier Skew, UpSta & Num, DnSta & Num=  ,4990, 2 ,4990, 2 , 0 , 0 , 0 ,,
       1       1
     100   104.6
       1       1
     100   104.8
Pier Skew, UpSta & Num, DnSta & Num=  ,5010, 2 ,5010, 2 , 0 , 0 , 0 ,,
       1       1
     100   104.8
       1       1
     100   104.7
BR Coef=-1 , 0 , 0 ,, 0 ,,,.8,0,,0,
WSPro=,,,, 1 ,,,, 0 ,,,, 0 ,,,,-1 ,-1 ,-1 , 0 , 0 , 0 , 0 , 0
BC Design=,, 0 ,, 0 ,,,,,,
BC HTab HWMax=107.5

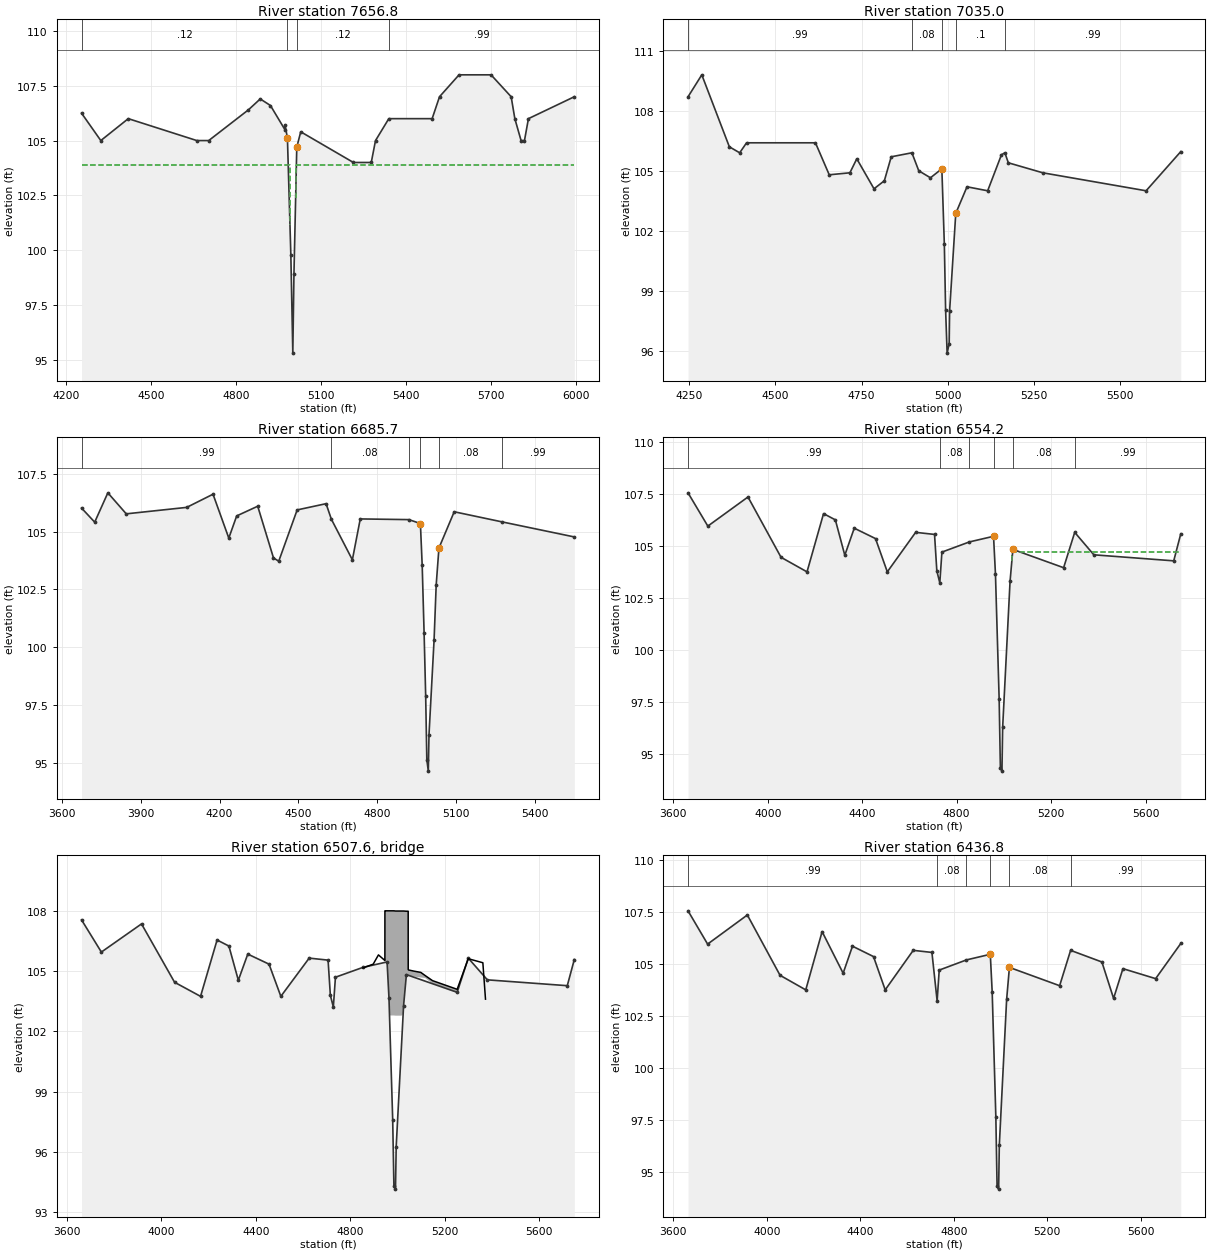
Type RM Length L Ch R = 1 ,7656.8  ,589.7,598.5,706.8
BEGIN DESCRIPTION:
Added Case No. 08-06-1925P
END DESCRIPTION:
XS GIS Cut Line= 5
 3066119.945791713890711.9080079      3066053.98      13890695.4
      3065546.09      13890568.3      3065215.48      13890568.3
      3064406.76      13890362.4
#Sta/Elev= 30
    4254  106.25    4322     105    4419     106    4661     105    4703     105
    4843   106.4    4885   106.9    4921   106.6    4972   105.5    4973   105.7
    4981   105.1    4993    99.8    5000    95.3    5004    98.9    5014   104.7
    5028   105.4    5214     104    5277     104    5292     105    5339     106
    5492     106    5518     107    5587     108    5700     108    5771     107
    5784     106    5806     105    5818     105    5832     106    5994     107
#Mann= 4 ,-1 , 0
    4254     .12       0    4981     .04       0    5014     .12       0
    5339     .99       0
#XS Ineff= 2 , 0
       0    4990   103.9    5010       0   103.9
Permanent Ineff=
       F       F
Bank Sta=4981,5014
XS Rating Curve= 0
Exp/Cntr=.3,.1

Type RM Length L Ch R = 1 ,7035.0  ,371.3,349.3,324.9
BEGIN DESCRIPTION:
Cross Section Xsec7.0
Located At: US RODNEY RAY BLVD
END DESCRIPTION:
XS GIS Cut Line= 2
  3066259.52250513890537.9603006       3065111.1      13889684.6
#Sta/Elev= 30
  4246.3   108.7  4286.3   109.8  4366.3   106.2  4396.3   105.9  4416.3   106.4
  4616.3   106.4  4656.3   104.8  4716.3   104.9  4736.3   105.6  4786.3   104.1
  4816.3   104.5  4836.3   105.7  4896.3   105.9  4916.3     105  4950.2  104.65
  4983.3   105.1  4990.5  101.33  4994.2   98.05  4998.6   95.88  5004.6   96.36
  5005.8   97.99  5023.7  102.87  5056.3   104.2  5116.3     104  5156.3   105.8
  5166.3   105.9  5176.3   105.4  5276.3   104.9  5576.3     104    5677  105.96
#Mann= 5 ,-1 , 0
  4246.3     .99       0  4896.3     .08       0  4983.3     .04       0
  5023.7      .1       0  5166.3     .99       0
Bank Sta=4983.3,5023.7
XS Rating Curve= 0
Exp/Cntr=.3,.1

Type RM Length L Ch R = 1 ,6685.7  ,127.9,131.5,126.9
BEGIN DESCRIPTION:
Rodney Ray Blvd. - 4
Interpolated channel, LIDAR overbanks
END DESCRIPTION:
XS GIS Cut Line= 4
      3066988.28      13890384.6      3066048.37     13889799.14
      3065487.37     13889787.23      3065281.82     13889782.19
#Sta/Elev= 30
    3675  106.02    3725  105.41    3775  106.68    3845  105.77    4075  106.05
    4175  106.62    4235  104.72    4265  105.68    4345   106.1    4405  103.86
    4425  103.72    4495  105.94    4605  106.21    4625  105.54    4705  103.78
    4735  105.55    4920  105.52 4963.72  105.35 4970.54  103.54 4977.86  100.59
 4983.78    97.9 4988.15   95.13 4993.78   94.63 4996.41    96.2 5015.81  100.32
 5023.79  102.69 5034.23  104.29  5092.3  105.86    5275  105.42  5549.1  104.77
#Mann= 6 ,-1 , 0
    3675     .99       0    4625     .08       0    4920     .04       0
 4963.72     .04       0 5034.23     .08       0    5275     .99       0
Bank Sta=4963.72,5034.23
XS Rating Curve= 0
Exp/Cntr=.5,.3

Type RM Length L Ch R = 1 ,6554.2  ,117,117.4,120.8
BEGIN DESCRIPTION:
Rodney Ray Blvd. - 3
END DESCRIPTION:
XS GIS Cut Line= 3
      3067083.17     13890304.99      3066119.96       13889705.
      3065171.99      13889683.6
#Sta/Elev= 30
  3662.6  107.54  3746.5  105.94  3916.5  107.34  4056.5  104.44  4166.5  103.74
  4236.5  106.54  4286.5  106.24  4326.5  104.54  4366.5  105.84  4456.5  105.34
  4506.5  103.74  4626.5  105.64  4706.5  105.54  4716.2  103.79  4728.8  103.21
  4737.7  104.694854.201  105.184956.345  105.454964.427  103.64 4980.12   97.62
4985.288   94.324991.959   94.164994.967   96.275026.258  103.285038.192  104.82
  5253.1  103.945300.085  105.64    5381  104.56  5719.4  104.27  5749.2  105.57
#Mann= 6 ,-1 , 0
  3662.6     .99       0  4728.8     .08       04854.201     .04       0
4956.345     .04       05038.192     .08       05300.085     .99       0
#XS Ineff= 2 , 0
       0  4955.9   104.7  5033.9       0   104.7
Permanent Ineff=
       F       F
Bank Sta=4956.345,5038.192
XS Rating Curve= 0
Skew Angle= 20
Exp/Cntr=.5,.3

Type RM Length L Ch R = 3 ,6507.6  ,,,
BEGIN DESCRIPTION:
RODNEY RAY BLVD
Structure ID: E125-00-00-04
END DESCRIPTION:
Bridge Culvert--1,0,-1,-1, 0
Deck Dist Width WeirC Skew NumUp NumDn MinLoCord MaxHiCord MaxSubmerge Is_Ogee
10,98.4,2.6,20, 39, 39, , , .95, 0, ,,,
  4854.2 4897.62 4919.79 4945.26 4947.03 4947.14 4947.24 4956.35 4964.43 4968.01
 4968.09 4971.94 4980.12 4983.03 4983.14 4985.29 4991.96 4994.31 4994.41 4994.97
 5017.14 5024.37 5024.47 5026.26 5038.19 5045.52 5045.63 5045.73 5045.83  5047.5
 5071.27 5099.08 5117.97 5148.79 5173.23  5253.1 5300.09 5361.92  5373.1
  105.15  105.34   105.8  105.54  105.52  107.99  107.99  107.99  107.99  107.99
  107.99  107.99  107.99  107.99  107.99  107.99  107.98  107.98  107.98  107.98
  107.98  107.98  107.98  107.98  107.97  107.97  107.97  107.97  105.07  105.05
  104.99  104.93  104.77  104.52  104.42  104.09  105.61  105.41   103.6
  105.14  105.33  105.79  105.53  105.51  105.51   105.5  105.41   103.6  102.23
  102.79  102.79  102.79  102.79  102.79  102.79  102.78  102.78  102.78  102.78
  102.78  102.78   102.7  103.24  104.78  104.77  104.77  104.77  104.77  104.76
  104.72  104.68  104.65  104.32  104.05   103.9   105.6   105.4   103.6
  4854.2 4897.62 4919.79 4945.26 4947.03 4947.14 4947.24 4956.35 4964.43 4968.01
 4968.09 4971.94 4980.12 4983.03 4983.14 4985.29 4991.96 4994.31 4994.41 4994.97
 5017.14 5024.37 5024.47 5026.26 5038.19 5045.52 5045.63 5045.73 5045.83  5047.5
 5071.27 5099.08 5117.97 5148.79 5173.23  5253.1 5300.09 5361.92  5373.1
  105.15  105.34   105.8  105.54  105.52  107.99  107.99  107.99  107.99  107.99
  107.99  107.99  107.99  107.99  107.99  107.99  107.98  107.98  107.98  107.98
  107.98  107.98  107.98  107.98  107.97  107.97  107.97  107.97  105.07  105.05
  104.99  104.93  104.77  104.52  104.42  104.09  105.61  105.41   103.6
  105.14  105.33  105.79  105.53  105.51  105.51   105.5  105.41   103.6  102.23
  102.79  102.79  102.79  102.79  102.79  102.79  102.78  102.78  102.78  102.78
  102.78  102.78   102.7  103.24  104.78  104.77  104.77  104.77  104.77  104.76
  104.72  104.68  104.65  104.32  104.05   103.9   105.6   105.4   103.6
BR Coef= 1 , 1 , 0 ,1.25, 0 ,,,.8,0,2,0,
WSPro=,,,, 1 ,,,, 0 ,,,, 0 ,,,,-1 ,-1 ,-1 , 0 , 0 , 0 , 0 , 0
BR D #Sta/Elev= 112
  3662.6  107.54  3666.5  106.84  3672.6  106.77  3732.6   106.1  3746.5  105.94
  3748.3  105.95  3916.5  107.34  3932.6  106.91  3946.5  106.54  3992.6  106.02
  4026.5  105.64  4056.5  104.44  4082.6  104.09  4086.5  104.04  4126.5  104.14
  4132.6  104.08  4152.6  103.88  4166.5  103.74  4172.6  104.17  4186.5  105.14
  4192.6  105.31  4212.6  105.87  4236.5  106.54  4286.5  106.24  4292.6  105.98
  4312.6  105.13  4326.5  104.54  4332.6  104.63  4346.5  104.84  4362.6  105.65
  4366.5  105.84  4392.6   105.7  4456.5  105.34  4472.6  104.82  4506.5  103.74
  4542.6  104.14  4596.5  104.74  4626.5  105.64  4692.6  105.56  4702.6  105.54
  4706.5  105.54  4716.2  103.79  4728.8  103.21  4737.7  104.69  4772.6  104.83
  4813.7     105  4854.2  105.18 4897.62  105.37 4919.79  105.83 4945.26  105.57
 4947.03  105.55 4947.14  105.55 4947.24  105.54 4956.35  105.45 4964.43  103.64
 4968.01  102.27 4968.09  102.23 4971.94  100.76 4980.12   97.62 4983.03   95.84
 4983.14   95.84 4985.29   94.32 4991.96   94.16 4994.31   95.89 4994.41   95.89
 4994.97   96.27 5017.14  100.52 5024.37  102.71 5024.47  102.74 5026.26  103.28
 5038.19  104.82 5045.52  104.81 5045.63  104.81 5045.73  104.81 5045.83  104.81
  5047.5   104.8 5071.27  104.76 5099.08  104.72 5117.97  104.69 5148.79  104.36
 5173.23  104.09  5253.1  103.94 5300.09  105.64 5361.92  105.44    5381  104.56
  5389.4  104.55  5409.4  104.87  5419.4     105  5429.4  105.02  5439.4  104.95
  5449.4  104.81  5459.4  104.75  5469.4  104.75  5479.4  104.66  5509.4  104.64
  5519.4  104.66  5529.4  104.72  5539.4  104.91  5549.4  105.03  5559.4  105.09
  5569.4  104.87  5579.4  104.77  5629.4  104.77  5639.4  104.82  5679.4  104.73
  5689.4  104.76  5699.4  104.63  5709.4  104.54  5719.4  104.27  5729.4   104.7
  5739.4  105.49  5749.2  105.57
BR D #Mann= 6
  3662.6     .99  4728.8     .08  4854.2     .04 4956.35     .04 5038.19     .08
 5300.09     .99
BR D Banks=4956.35,5038.19
BC Design=,, 0 ,, 0 ,,,,,,
BC HTab HWMax=107.54

Type RM Length L Ch R = 1 ,6436.8  ,112.2,110.5,104.1
BEGIN DESCRIPTION:
Rodney Ray Blvd. - 2
END DESCRIPTION:
XS GIS Cut Line= 3
      3067131.57     13890199.94       3066167.2     13889599.23
      3065199.52      13889578.8
#Sta/Elev= 30
  3662.6  107.54  3746.5  105.94  3916.5  107.34  4056.5  104.44  4166.5  103.74
  4236.5  106.54  4326.5  104.54  4366.5  105.84  4456.5  105.34  4506.5  103.74
  4626.5  105.64  4706.5  105.54  4728.8  103.21  4737.7  104.694854.201  105.18
4956.345  105.454964.427  103.64 4980.12   97.624985.288   94.324991.959   94.16
4994.967   96.275026.258  103.285038.192  104.82  5253.1  103.945300.085  105.64
    5434  105.08    5484  103.33    5524  104.76    5664  104.28  5771.6  105.97
#Mann= 6 ,-1 , 0
  3662.6     .99       0  4728.8     .08       04854.201     .04       0
4956.345     .04       05038.192     .08       05300.085     .99       0
#XS Ineff= 2 , 0
       0  4955.9     104  5033.9       0     104
Permanent Ineff=
       F       F
Bank Sta=4956.345,5038.192
XS Rating Curve= 0
Skew Angle= 20
Exp/Cntr=.5,.3