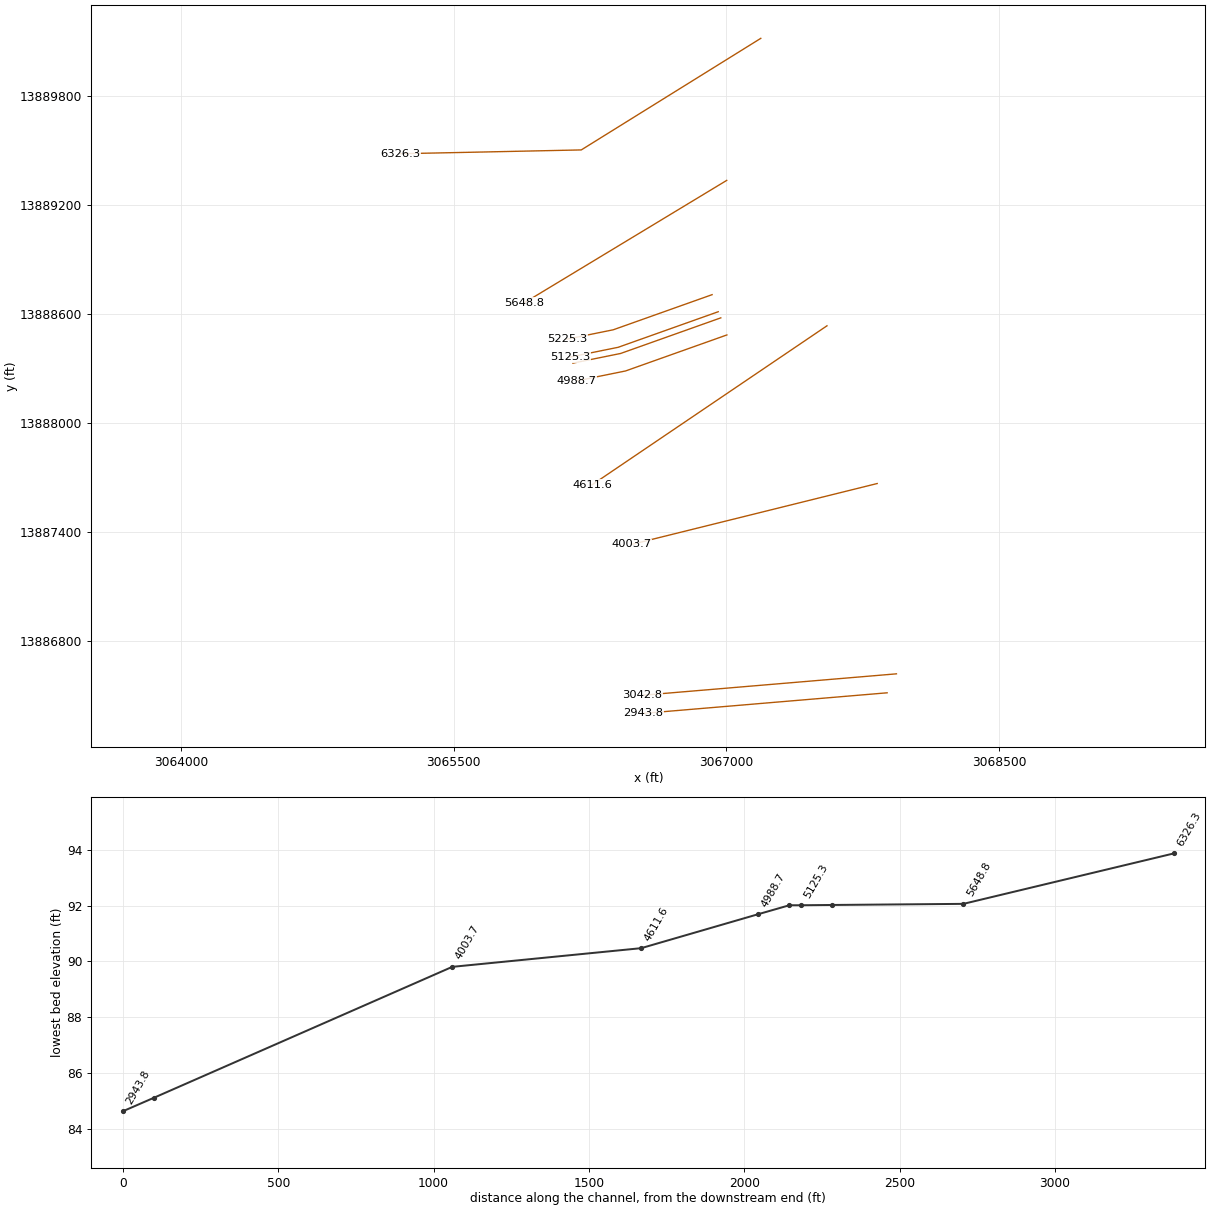
HEC-RAS study E125-00-00.prj: E125-00-00

--- E125-00-00.g01 (geometry) --- (continued)

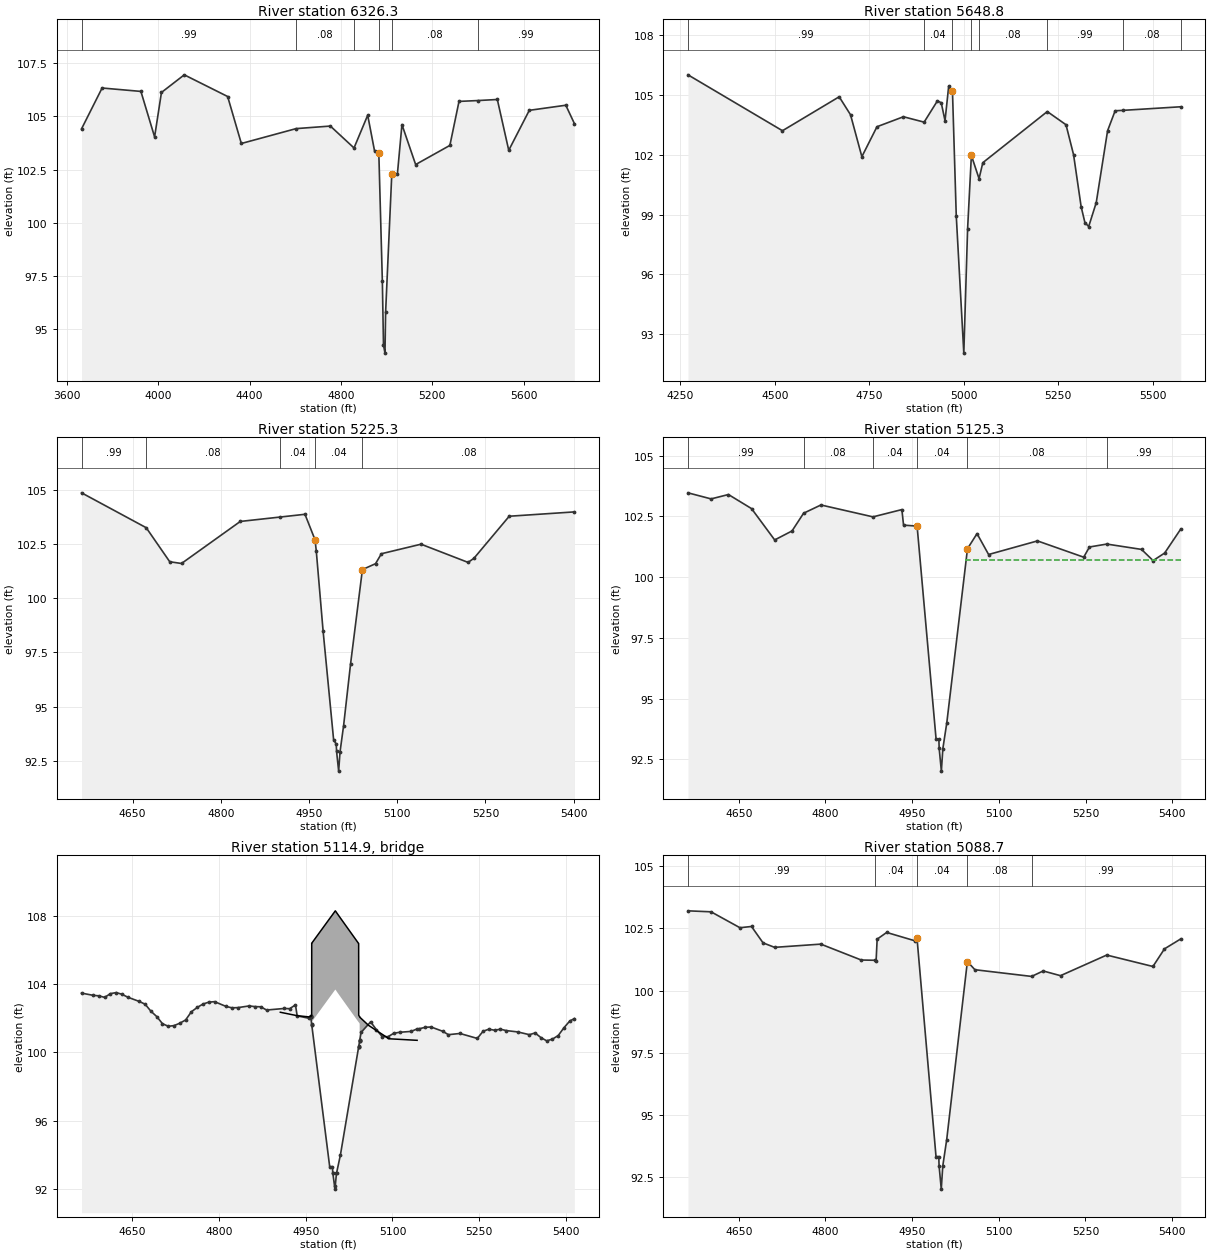
Type RM Length L Ch R = 1 ,6326.3  ,659.2,677.5,701.3
BEGIN DESCRIPTION:
Rodney Ray Blvd. - 1
Interpolated channel, LIDAR overbanks
END DESCRIPTION:
XS GIS Cut Line= 4
       3067189.7      13890120.3      3066202.02     13889505.08
      3065584.32     13889491.96      3065206.85     13889484.15
#Sta/Elev= 30
  3663.8  104.42  3753.8  106.34  3923.8  106.18  3983.8  104.04  4013.8  106.13
  4113.8  106.96  4303.8  105.94  4363.8  103.73  4603.8  104.43  4753.8  104.55
  4857.4  103.52  4917.4  105.06  4947.4  103.38 4966.16  103.26 4981.51   97.28
 4986.56   94.25 4993.08   93.87 4995.85   95.79 5022.92   102.3  5047.4  102.28
  5067.4  104.62  5127.4  102.74  5277.4  103.64  5317.4  105.71    5400  105.75
  5485.3   105.8  5535.3  103.41  5625.3  105.29  5785.3  105.53  5822.8  104.67
#Mann= 6 ,-1 , 0
  3663.8     .99       0  4603.8     .08       0  4857.4     .04       0
 4966.16     .04       0 5022.92     .08       0    5400     .99       0
#XS Ineff= 2 , 0
       0    4925  104.05               0
Permanent Ineff=
       F       F
Bank Sta=4966.16,5022.92
XS Rating Curve= 0
Exp/Cntr=.3,.1

Type RM Length L Ch R = 1 ,5648.8  ,427.8,423.5,414.2
BEGIN DESCRIPTION:
Cross Section Xsec06-residential drainage to creek on right, not using blocked obstruction
Located At: US MAUNA LOA ST
END DESCRIPTION:
XS GIS Cut Line= 2
      3067002.29     13889337.17       3065887.4      13888661.6
#Sta/Elev= 30
  4270.3     106  4520.3   103.2  4670.3   104.9  4700.3     104  4730.3   101.9
  4770.3   103.4  4840.3   103.9    4895  103.63  4930.3   104.7  4940.3   104.6
  4950.3   103.7 4959.98  105.43    4970  105.17    4980   98.94 4999.99   92.06
    5010   98.28    5020  101.96  5040.3   100.8  5050.3   101.6  5220.8  104.16
  5270.3   103.5  5290.3     102  5310.3    99.4  5320.3    98.6  5330.3    98.4
  5350.3    99.6  5380.3   103.2  5400.3   104.2  5420.8  104.22  5573.9   104.4
#Mann= 8 ,-1 , 0
  4270.3     .99       0    4895     .04       0    4970     .04       0
    5020     .04       0  5040.3     .08       0  5220.8     .99       0
  5420.8     .08       0  5573.9      .2       0
#XS Ineff= 2 , 0
       0 4959.98  105.43 5201.59       0  102.01
Permanent Ineff=
       F       F
Bank Sta=4970,5020
XS Rating Curve= 0
Exp/Cntr=.3,.1

Type RM Length L Ch R = 1 ,5225.3  ,100.2,100,99.8
BEGIN DESCRIPTION:
Bicycle Ridge - 4
Interpolated channel, LIDAR overbanks
END DESCRIPTION:
XS GIS Cut Line= 3
      3066921.87      13888707.1      3066377.94     13888513.43
       3066122.4      13888461.5
#Sta/Elev= 25
  4563.1  104.86  4673.1  103.25  4713.1  101.68  4733.1   101.6  4833.1  103.54
    4900  103.74  4943.1  103.87 4960.24  102.69 4962.29  102.19 4973.94   98.48
  4991.8   93.47 4996.34   93.26 4996.81   92.94  5000.4   92.02 5002.73   92.91
  5008.8   94.12 5020.61   96.96 5040.79  101.32  5063.1  101.59  5073.1  102.05
  5140.5  102.49  5220.5  101.65  5230.5  101.84  5290.5  103.78  5401.3  103.98
#Mann= 5 ,-1 , 0
  4563.1     .99       0  4673.1     .08       0    4900     .04       0
 4960.24     .04       0 5040.79     .08       0
Bank Sta=4960.24,5040.79
XS Rating Curve= 0
Exp/Cntr=.5,.3

Type RM Length L Ch R = 1 ,5125.3  ,36.6,36.6,36.6
BEGIN DESCRIPTION:
Bicycle Ridge - 3
END DESCRIPTION:
XS GIS Cut Line= 3
      3066955.43     13888612.98      3066404.81     13888416.85
      3066142.31     13888363.51
#Sta/Elev= 30
  4562.2  103.47  4602.2  103.22  4632.2   103.4  4672.2  102.82  4712.2  101.53
  4742.2   101.9  4762.2  102.63  4792.2  102.97  4882.2  102.48  4932.2  102.78
  4935.1  102.14  4958.1   102.1  4958.5  102.11  4991.4   93.32  4996.2   93.32
  4996.7   92.95  5000.5   92.01  5003.1   92.94  5009.9      94  5045.7  101.17
  5062.2  101.79  5082.2  100.93  5166.7  101.49  5246.7  100.82  5256.7  101.24
  5286.7  101.36  5346.7  101.14  5366.7  100.68  5386.7  100.99  5414.6  101.98
#Mann= 6 ,-1 , 0
  4562.2     .99       0  4762.2     .08       0  4882.2     .04       0
  4958.1     .04       0  5045.7     .08       0  5286.7     .99       0
#XS Ineff= 2 , 0
       0  4960.2  100.75  5043.2       0   100.7
Permanent Ineff=
       F       F
Bank Sta=4958.5,5045.7
XS Rating Curve= 0
Exp/Cntr=.5,.3

Type RM Length L Ch R = 3 ,5114.9  ,,,
BEGIN DESCRIPTION:
BICYCLE BRIDGE
Structure ID: E125-00-00-03
END DESCRIPTION:
Bridge Culvert--1,0,-1,-1, 0
Deck Dist Width WeirC Skew NumUp NumDn MinLoCord MaxHiCord MaxSubmerge Is_Ogee
10,6.8,2.6,0, 33, 33, , , .95, 0, ,,,
    4906  4935.1  4955.4  4958.1 4958.21  4958.3  4958.4  4958.5 4960.18 4960.19
  4960.3 4960.41  4991.4  4996.2  4996.7 4996.81  5000.5  5001.1  5003.1 5003.21
  5009.9 5041.39  5041.5 5041.61 5043.19  5043.3 5043.41  5043.5  5045.7  5058.7
 5058.81    5094  5142.6
  102.35  102.15  102.08  102.12  102.11   102.1  102.12  102.11  102.19  102.19
  106.39  106.39  107.83  108.05  108.08  108.08  108.25  108.28  108.19  108.18
  107.86  106.37  106.37  102.17  102.09  102.08  102.06  102.06  101.99  101.58
  101.58   100.8  100.71
  102.34  102.14     102   102.1   102.1   102.1  102.11  102.11  101.66  101.79
  101.79  101.79  103.23  103.45  103.48  103.48  103.65  103.68  103.59  103.58
  103.26  101.77  101.77  101.77  101.69  100.69  100.71  100.73  101.17  100.84
  100.84  100.79  100.71
    4906  4935.1  4955.4  4958.1 4958.21  4958.3  4958.4  4958.5 4960.18 4960.19
  4960.3 4960.41  4991.4  4996.2  4996.7 4996.81  5000.5  5001.1  5003.1 5003.21
  5009.9 5041.39  5041.5 5041.61 5043.19  5043.3 5043.41  5043.5  5045.7  5058.7
 5058.81    5094  5142.6
  102.35  102.15  102.08  102.12  102.11   102.1  102.12  102.11  102.19  102.19
  106.39  106.39  107.83  108.05  108.08  108.08  108.25  108.28  108.19  108.18
  107.86  106.37  106.37  102.17  102.09  102.08  102.06  102.06  101.99  101.58
  101.58   100.8  100.71
  102.34  102.14     102   102.1   102.1   102.1  102.11  102.11  101.66  101.79
  101.79  101.79  103.23  103.45  103.48  103.48  103.65  103.68  103.59  103.58
  103.26  101.77  101.77  101.77  101.69  100.69  100.71  100.73  101.17  100.84
  100.84  100.79  100.71
BR Coef= 1 , 1 , 0 ,1.25, 0 ,,,.8,0,2,0,
WSPro=,,,, 1 ,,,, 0 ,,,, 0 ,,,,-1 ,-1 ,-1 , 0 , 0 , 0 , 0 , 0
BR U #Sta/Elev= 89
  4562.2  103.47  4582.2  103.34  4592.2  103.31  4602.2  103.22  4612.2  103.44
  4622.2   103.5  4632.2   103.4  4642.2  103.23  4662.2  102.98  4672.2  102.82
  4682.2  102.41  4692.2   102.1  4702.2  101.68  4712.2  101.53  4722.2  101.57
  4732.2  101.71  4742.2   101.9  4752.2  102.38  4762.2  102.63  4772.2  102.83
  4782.2  102.94  4792.2  102.97  4812.2  102.69  4822.2  102.61  4832.2  102.62
  4852.2  102.72  4862.2  102.68  4872.2  102.67  4882.2  102.48  4912.2  102.57
  4922.2  102.56  4932.2  102.78  4935.1  102.14  4955.4     102  4958.1   102.1
 4958.21   102.1  4958.3   102.1  4958.4  102.11  4958.5  102.11 4960.19  101.66
  4960.3  101.63 4960.41   101.6  4991.4   93.32  4996.2   93.32  4996.7   92.95
 4996.81   92.95  5000.5   92.01  5001.1   92.22  5003.1   92.94 5003.21   92.94
  5009.9      94 5041.39  100.31  5041.5  100.33 5041.61  100.35 5043.19  100.67
  5043.3  100.69 5043.41  100.71  5043.5  100.73  5045.7  101.17  5062.2  101.79
  5072.2  101.33  5082.2  100.93  5092.2  100.92  5102.2  101.12  5112.2  101.18
  5132.2  101.23  5142.2  101.37  5146.7  101.39  5156.7  101.47  5166.7  101.49
  5186.7  101.24  5196.7  101.04  5216.7  101.11  5246.7  100.82  5256.7  101.24
  5266.7  101.36  5276.7   101.3  5286.7  101.36  5296.7  101.28  5316.7   101.2
  5336.7  101.04  5346.7  101.14  5356.7  100.87  5366.7  100.68  5376.7  100.78
  5386.7  100.99  5396.7  101.45  5406.7  101.84  5414.6  101.98
BR U #Mann= 6
  4562.2     .99  4762.2     .08  4882.2     .04  4958.1     .04  5045.7     .08
  5286.7     .99
BR U Banks=4958.5,5045.7
BR D #Sta/Elev= 89
  4562.2  103.47  4582.2  103.34  4592.2  103.31  4602.2  103.22  4612.2  103.44
  4622.2   103.5  4632.2   103.4  4642.2  103.23  4662.2  102.98  4672.2  102.82
  4682.2  102.41  4692.2   102.1  4702.2  101.68  4712.2  101.53  4722.2  101.57
  4732.2  101.71  4742.2   101.9  4752.2  102.38  4762.2  102.63  4772.2  102.83
  4782.2  102.94  4792.2  102.97  4812.2  102.69  4822.2  102.61  4832.2  102.62
  4852.2  102.72  4862.2  102.68  4872.2  102.67  4882.2  102.48  4912.2  102.57
  4922.2  102.56  4932.2  102.78  4935.1  102.14  4955.4     102  4958.1   102.1
 4958.21   102.1  4958.3   102.1  4958.4  102.11  4958.5  102.11 4960.19  101.66
  4960.3  101.63 4960.41   101.6  4991.4   93.32  4996.2   93.32  4996.7   92.95
 4996.81   92.95  5000.5   92.01  5001.1   92.22  5003.1   92.94 5003.21   92.94
  5009.9      94 5041.39  100.31  5041.5  100.33 5041.61  100.35 5043.19  100.67
  5043.3  100.69 5043.41  100.71  5043.5  100.73  5045.7  101.17  5062.2  101.79
  5072.2  101.33  5082.2  100.93  5092.2  100.92  5102.2  101.12  5112.2  101.18
  5132.2  101.23  5142.2  101.37  5146.7  101.39  5156.7  101.47  5166.7  101.49
  5186.7  101.24  5196.7  101.04  5216.7  101.11  5246.7  100.82  5256.7  101.24
  5266.7  101.36  5276.7   101.3  5286.7  101.36  5296.7  101.28  5316.7   101.2
  5336.7  101.04  5346.7  101.14  5356.7  100.87  5366.7  100.68  5376.7  100.78
  5386.7  100.99  5396.7  101.45  5406.7  101.84  5414.6  101.98
BR D #Mann= 6
  4562.2     .99  4762.2     .08  4882.2     .04  4958.1     .04  5045.7     .08
  5286.7     .99
BR D Banks=4958.5,5045.7
BC Design=,, 0 ,, 0 ,,,,,,
BC HTab HWMax=103.5

Type RM Length L Ch R = 1 ,5088.7  ,100.2,100,100
BEGIN DESCRIPTION:
Bicycle Ridge - 2
END DESCRIPTION:
XS GIS Cut Line= 3
      3066969.55      13888579.2      3066418.61      13888382.9
      3066155.76      13888329.5
#Sta/Elev= 30
    4562  103.21    4602  103.17    4652  102.53    4672  102.58    4692  101.92
    4712  101.74    4792  101.87    4862  101.23  4886.1  101.22  4887.7   101.2
  4889.5  102.07    4906  102.34  4955.4     102  4958.1   102.1  4958.5  102.11
  4991.4   93.32  4996.2   93.32  4996.7   92.95  5000.5   92.01  5003.1   92.94
  5009.9      94  5045.7  101.17  5058.7  100.84  5156.9  100.57  5176.9  100.79
  5206.9   100.6  5286.9  101.43  5366.9  100.97  5386.9  101.68  5415.1  102.08
#Mann= 5 ,-1 , 0
    4562     .99       0  4886.1     .04       0  4958.1     .04       0
  5045.7     .08       0  5156.9     .99       0
#XS Ineff= 2 , 0
       0    4948   101.4    5053       0   100.8
Permanent Ineff=
       F       F
Bank Sta=4958.5,5045.7
XS Rating Curve= 0
Exp/Cntr=.5,.3

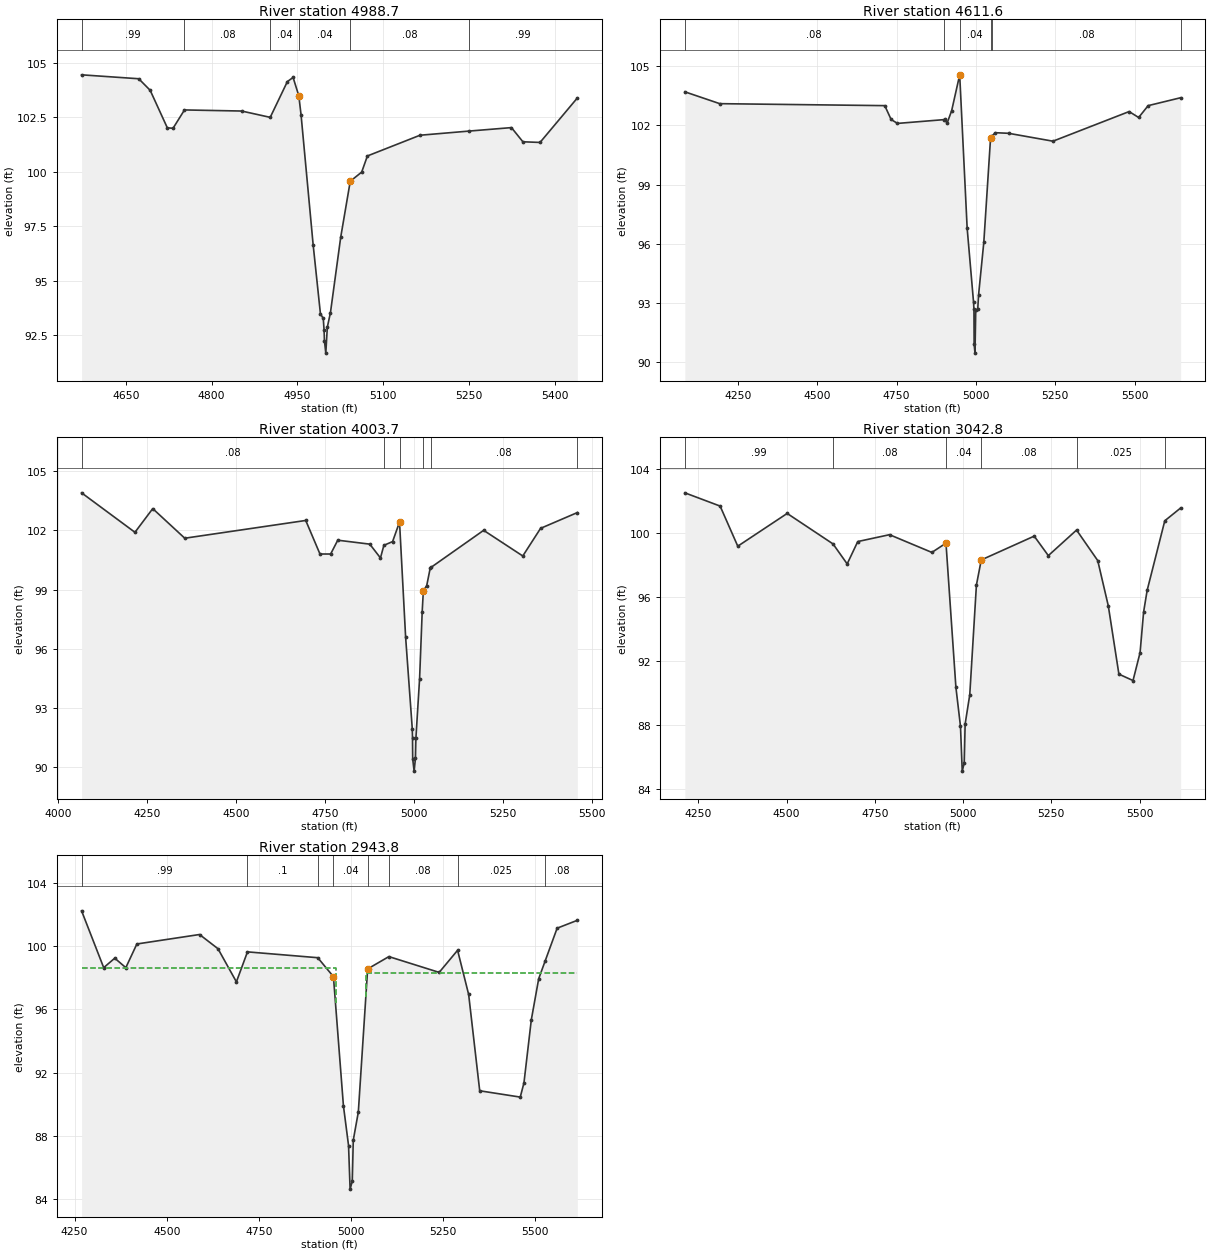
Type RM Length L Ch R = 1 ,4988.7  ,366.3,377.1,390.3
BEGIN DESCRIPTION:
Bicycle Ridge - 1
Interpolated channel, LIDAR overbanks
END DESCRIPTION:
XS GIS Cut Line= 3
      3067003.11       13888485.      3066445.48     13888286.38
      3066175.68     13888231.54
#Sta/Elev= 30
  4572.6  104.45  4672.6  104.27  4692.6  103.74  4722.6  102.02  4732.6     102
  4752.6  102.84  4852.6  102.79  4902.6   102.5  4932.6  104.14  4942.6  104.33
  4952.6  103.49 4956.53  102.62 4977.64   96.67 4990.45   93.49  4995.4   93.28
 4996.86   92.73  4997.4   92.26 4999.83   91.69 5002.48   92.88 5007.98   93.55
 5025.88      97  5042.6   99.57  5062.6   99.99  5072.6  100.73  5164.6  101.68
    5250  101.87  5324.6  102.03  5344.6  101.38  5374.6  101.35  5439.9  103.39
#Mann= 6 ,-1 , 0
  4572.6     .99       0  4752.6     .08       0  4902.6     .04       0
  4952.6     .04       0  5042.6     .08       0    5250     .99       0
Bank Sta=4952.6,5042.6
XS Rating Curve= 0
Exp/Cntr=.3,.1

Type RM Length L Ch R = 1 ,4611.6  ,619.4,607.9,592
BEGIN DESCRIPTION:
Cross Section Xsec 5.0
Located At: DS MAUNA LOA ST
END DESCRIPTION:
XS GIS Cut Line= 2
      3067553.73     13888535.43      3066260.86     13887658.33
#Sta/Elev= 28
    4083   103.7    4193   103.1    4713     103    4733   102.3    4753   102.1
  4898.4  102.29    4903   102.3  4909.1   102.1  4923.7  102.74  4949.1  104.56
  4972.6    96.8  4992.8   93.04    4994    92.7  4994.6   90.92  4997.3   90.47
  4999.7   92.65    5006    92.7  5008.5    93.4  5025.1   96.08  5046.4  101.37
  5051.5  101.46  5060.8  101.63    5103   101.6    5243   101.2    5483   102.7
    5513   102.4    5543     103  5645.3   103.4
#Mann= 6 ,-1 , 0
    4083     .08       0  4898.4     .04       0  4949.1     .04       0
  5046.4     .04       0  5051.5     .08       0  5645.3      .2       0
Bank Sta=4949.1,5046.4
XS Rating Curve= 0
Exp/Cntr=.3,.1

Type RM Length L Ch R = 1 ,4003.7  ,963,960.9,952
BEGIN DESCRIPTION:
Cross Section Xsec4.0
Located At: US WOODWIND LANE
END DESCRIPTION:
XS GIS Cut Line= 2
      3067830.16     13887665.85      3066477.87     13887329.78
#Sta/Elev= 30
  4065.2   103.9  4215.2   101.9  4265.2   103.1  4355.2   101.6  4695.2   102.5
  4735.2   100.8  4765.2   100.8  4785.2   101.5  4875.2   101.3  4905.2   100.6
  4914.8  101.24  4939.3  101.43  4958.8  102.42  4975.9   96.59  4994.6   91.95
  4995.3   91.47  4995.8   90.42  4999.8    89.8  5003.5   90.44  5004.8   91.47
  5015.2   94.49  5022.5   97.88  5025.7   98.93  5035.2    99.2  5045.2   100.1
  5047.9  100.13  5195.2     102  5305.2   100.7  5355.2   102.1  5458.6   102.9
#Mann= 6 ,-1 , 0
  4065.2     .08       0  4914.8     .04       0  4958.8     .04       0
  5025.7     .04       0  5047.9     .08       0  5458.6      .2       0
Bank Sta=4958.8,5025.7
XS Rating Curve= 0
Exp/Cntr=.3,.1

Type RM Length L Ch R = 1 ,3042.8  ,98.7,99,100.2
BEGIN DESCRIPTION:
Woodwind Lane - 4
Interpolated channel, LIDAR overbanks
END DESCRIPTION:
XS GIS Cut Line= 2
      3067935.92      13886616.6        3066536.     13886498.22
#Sta/Elev= 30
  4211.5  102.52  4311.5  101.69  4361.5   99.18  4501.5  101.23  4631.5   99.32
  4671.5   98.07  4701.5   99.47  4791.5    99.9  4911.5   98.79  4951.5   99.37
 4979.59   90.35 4992.62    87.9 4997.53    85.1 5003.18   85.61 5005.77   88.05
 5018.88   89.88 5037.75   96.75  5051.5   98.32  5201.5   99.81  5241.5   98.59
  5321.5  100.19  5381.5   98.28  5411.5   95.44  5441.5   91.17  5481.5   90.77
  5501.5   92.52  5511.5   95.06  5521.5   96.41  5571.5  100.77  5616.4  101.57
#Mann= 6 ,-1 , 0
  4211.5     .99       0  4631.5     .08       0  4951.5     .04       0
  5051.5     .08       0  5321.5    .025       0  5571.5     .08       0
#Block Obstruct= 2 , 0
       0                  5321.5       0  100.19
Bank Sta=4951.5,5051.5
XS Rating Curve= 0
Exp/Cntr=.5,.3

Type RM Length L Ch R = 1 ,2943.8  ,55.1,56,56.8
BEGIN DESCRIPTION:
Woodwind Lane - 3
Detention pond on right VRR
END DESCRIPTION:
XS GIS Cut Line= 2
 3067884.7769485  13886512.01714      3066544.43     13886398.58
#Sta/Elev= 30
  4268.9  102.25  4328.9   98.65  4358.9   99.25  4388.9   98.65  4418.9  100.15
  4588.9  100.75  4638.9   99.85  4688.9   97.75  4718.9   99.65  4909.6   99.28
  4952.1   98.08  4979.2    89.9  4993.1   87.38  4997.3   84.62  5003.2   85.12
  5005.9   87.72  5019.6    89.5  5044.9   98.57  5102.5   99.35  5238.9   98.35
  5288.9   99.75  5318.9   96.95  5348.9   90.85  5458.9   90.45  5468.9   91.35
  5488.9   95.35  5508.9   97.95  5526.7   99.09  5558.9  101.15  5613.8  101.65
#Mann= 8 ,-1 , 0
  4268.9     .99       0  4718.9      .1       0  4909.6     .04       0
  4952.1     .04       0  5044.9     .04       0  5102.5     .08       0
  5288.9    .025       0  5526.7     .08       0
#XS Ineff= 2 , 0
       0    4958   98.63    5040       0    98.3
Permanent Ineff=
       F       F
#Block Obstruct= 2 , 0
       0                 5288.87       0    99.7
Bank Sta=4952.1,5044.9
XS Rating Curve= 0
Exp/Cntr=.5,.3