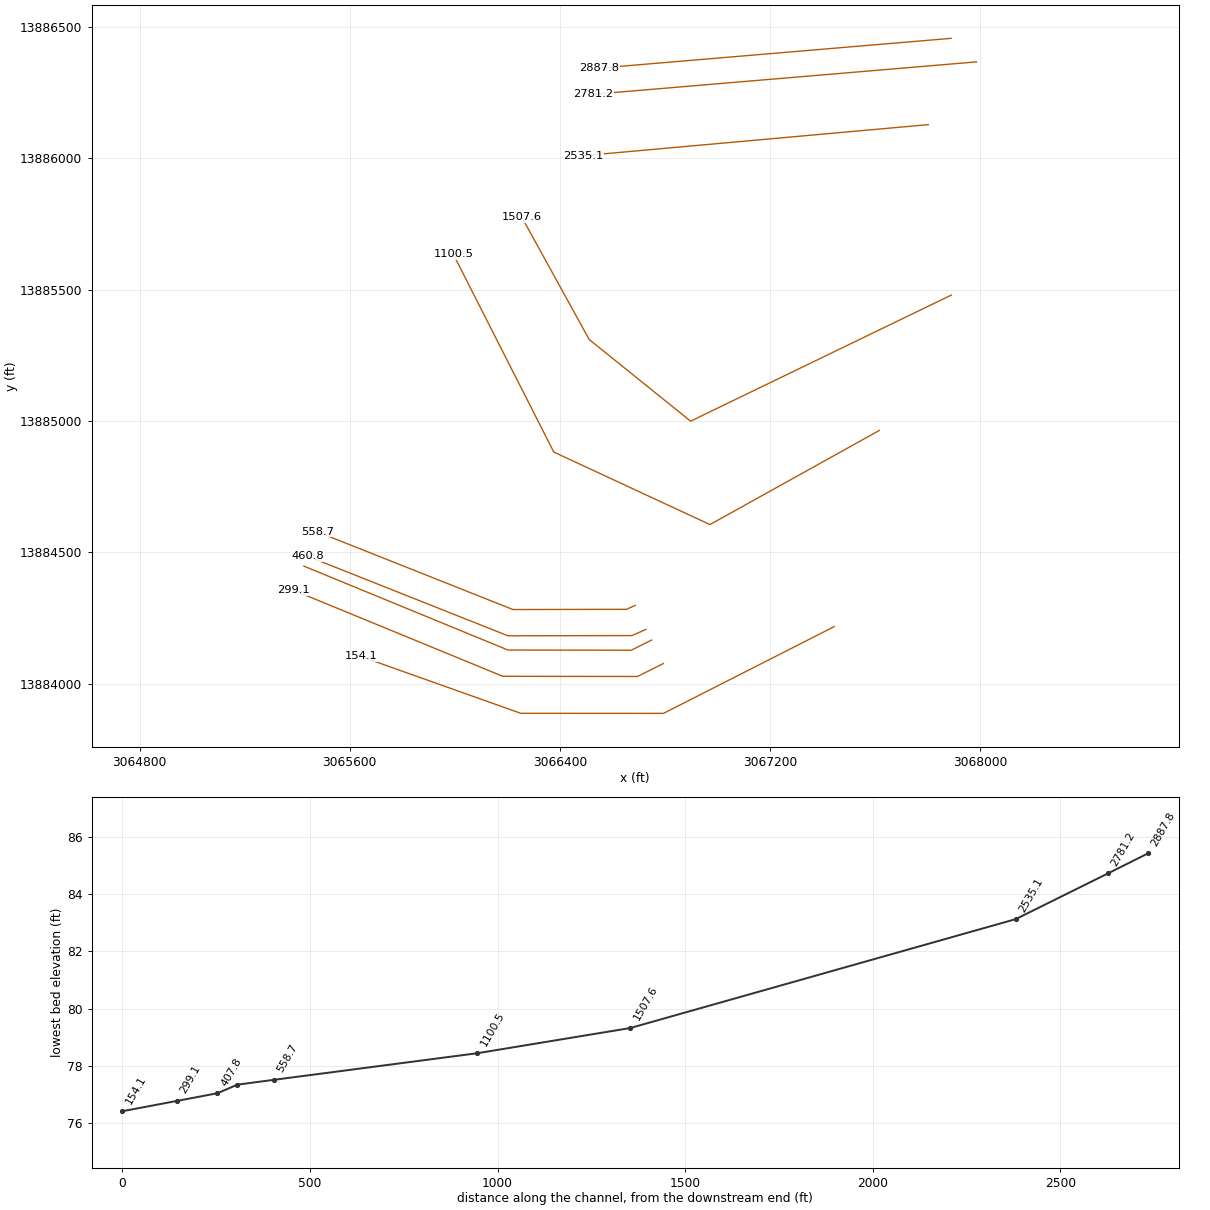
HEC-RAS study E125-00-00.prj: E125-00-00

--- E125-00-00.g01 (geometry) --- (continued)

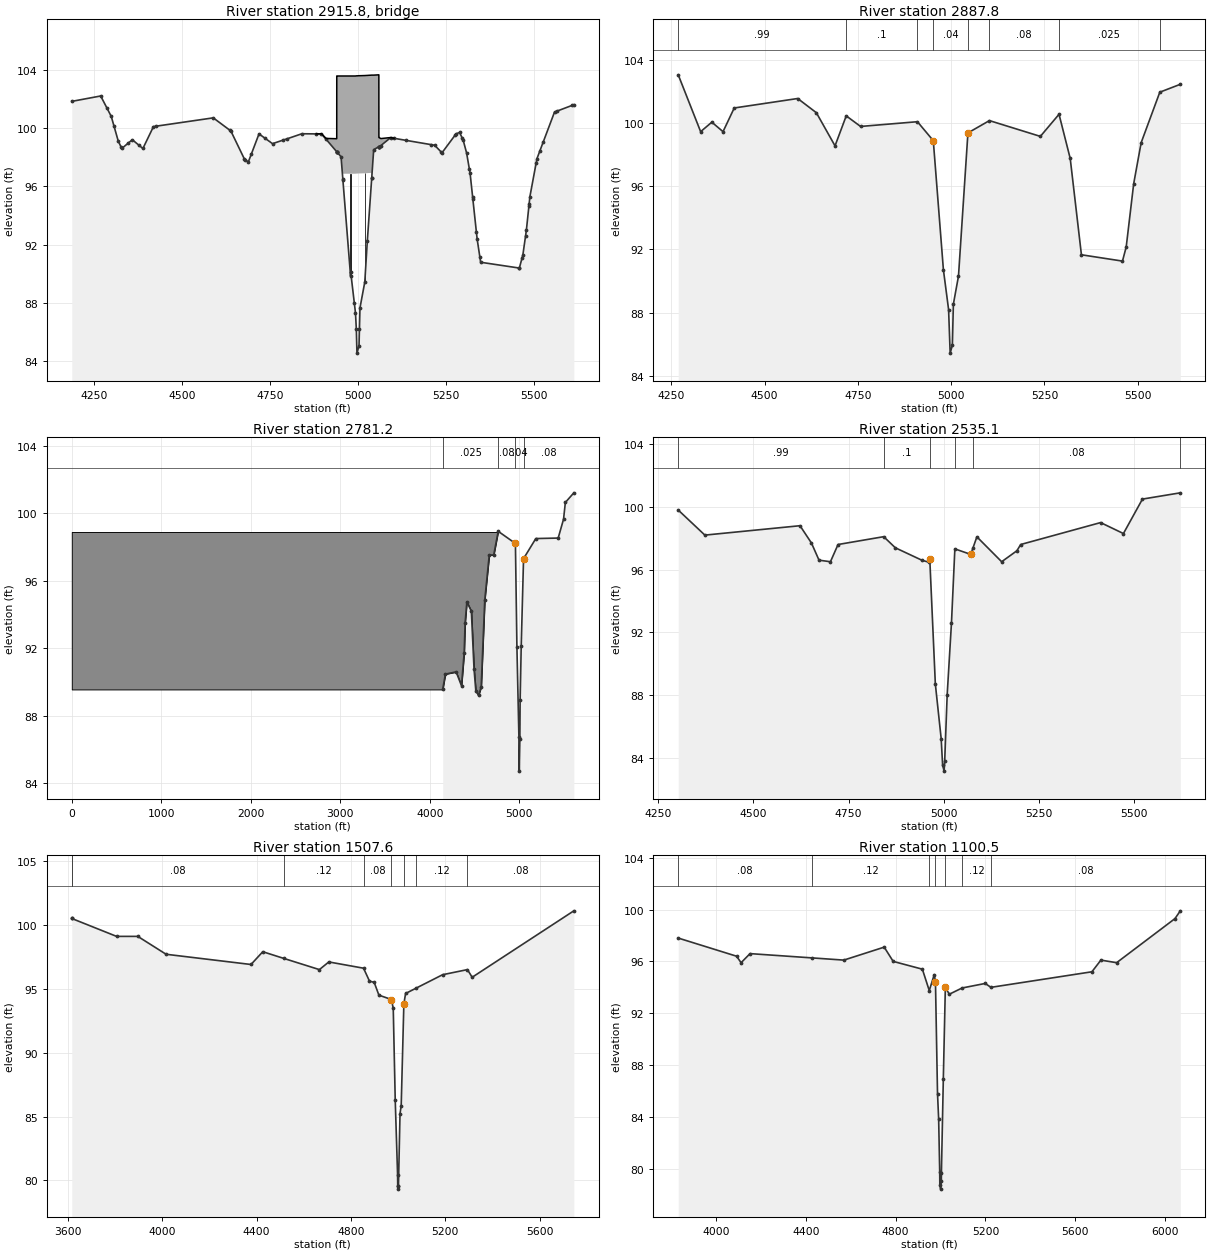
Type RM Length L Ch R = 3 ,2915.8  ,,,
BEGIN DESCRIPTION:
WOODWIND LANE
Structure ID: E125-00-00-02
END DESCRIPTION:
Bridge Culvert--1,0,-1,-1, 0
Deck Dist Width WeirC Skew NumUp NumDn MinLoCord MaxHiCord MaxSubmerge Is_Ogee
10,36,2.6,0, 31, 29, , , .95, 0, ,,,
  4881.4  4896.4  4909.6  4939.7 4939.79  4939.9 4940.01  4952.1 4957.21  4957.3
  4979.2  4979.6  4989.8  4993.1  4995.5  4997.3  5003.2  5004.4  5005.9  5019.6
  5026.7 5039.19  5039.3  5044.9 5059.49  5059.6 5059.71    5060  5065.3  5092.9
  5102.5
    99.6   99.61   99.29   99.27   99.27  103.57  103.57  103.57  103.57  103.57
  103.57  103.57  103.57  103.57  103.58  103.58  103.59  103.59  103.59   103.6
  103.61  103.63  103.63  103.63  103.65  103.65   99.35   99.35   99.28   99.35
    99.3
    99.6    99.6   99.23   98.38   98.38   98.37   98.37   98.03   96.49   96.87
   96.87   96.87   96.87   96.87   96.88   96.88   96.89   96.89   96.89    96.9
   96.91   96.93   96.58   98.52   98.72   98.72   98.72   98.73    98.8   99.34
    99.3
  4881.4  4896.4  4909.6  4939.7 4939.79  4939.9 4940.01  4952.1 4957.21  4957.3
  4979.2  4979.6  4989.8  4993.1  4995.5  4997.3  5003.2  5004.4  5005.9  5019.6
  5026.7 5039.19  5039.3  5044.9 5059.49  5059.6 5059.71    5060 5092.87
    99.6   99.61   99.29   99.27   99.27  103.57  103.57  103.57  103.57  103.57
  103.57  103.57  103.57  103.57  103.58  103.58  103.59  103.59  103.59   103.6
  103.61  103.63  103.63  103.63  103.65  103.65   99.35   99.35100.2694
    99.6    99.6   99.23   98.38   98.38   98.37   98.37   98.03   96.49   96.87
   96.87   96.87   96.87   96.87   96.88   96.88   96.89   96.89   96.89    96.9
   96.91   96.93   96.58   98.52   98.72   98.72   98.72   98.73
Pier Skew, UpSta & Num, DnSta & Num=  ,4979.2, 2 ,4979.2, 2 , 0 , 0 , 0 ,,
     1.3     1.3
   89.05   97.87
     1.3     1.3
   89.98    98.8
Pier Skew, UpSta & Num, DnSta & Num=  ,5019.6, 2 ,5019.6, 2 , 0 , 0 , 0 ,,
     1.3     1.3
   88.37    97.9
     1.3     1.3
    89.3   98.83
BR Coef= 1 , 1 , 1 ,1.25, 0 ,,,.8,0,2,0,
WSPro=,,,, 1 ,,,, 0 ,,,, 0 ,,,,-1 ,-1 ,-1 , 0 , 0 , 0 , 0 , 0
BR U #Sta/Elev= 94
  4186.7  101.83  4268.9   102.2  4286.7  101.37  4298.9   100.8  4306.7  100.14
  4318.9    99.1  4326.7   98.71  4328.9    98.6  4346.7   98.96  4358.9    99.2
  4376.7   98.84  4388.9    98.6  4418.9   100.1  4426.7  100.13  4588.9   100.7
  4636.7   99.84  4638.9    99.8  4676.7   97.91  4678.9    97.8  4688.9    97.7
  4696.7   98.19  4718.9    99.6  4736.7   99.29  4757.3   98.93  4786.7   99.17
  4798.3   99.26  4840.7   99.61  4881.4    99.6  4896.4    99.6  4909.6   99.23
  4939.7   98.38 4939.79   98.38  4939.9   98.37 4940.01   98.37  4952.1   98.03
 4957.21   96.49  4957.3   96.46  4979.2   89.85  4979.6   90.11  4989.8   88.01
  4993.1   87.33  4995.5   86.23  4997.3   84.57  5003.2   85.07  5004.4   86.25
  5005.9   87.67  5019.6   89.45  5026.7   92.23 5039.19   96.55  5039.3   96.58
  5044.9   98.52 5059.49   98.72  5059.6   98.72 5059.71   98.72    5060   98.73
  5065.3    98.8  5092.9   99.34  5102.5    99.3    5136   99.16  5206.7   98.87
  5218.2   98.82  5236.7   98.36  5238.9    98.3  5276.7   99.53  5278.9    99.6
  5288.9    99.7  5296.7   99.31  5298.9    99.2  5308.9    98.3  5316.7   97.21
  5318.9    96.9  5326.1   95.28  5326.7   95.14  5336.7   92.89  5338.9    92.4
  5346.7   91.15  5348.9    90.8  5456.7   90.41  5458.9    90.4  5466.7    91.1
  5468.9    91.3  5476.7   92.63  5478.9      93    5486   94.63  5486.7   94.79
  5488.9    95.3  5506.7   97.61  5508.9    97.9  5516.7    98.4  5526.7   99.04
  5558.9   101.1  5566.7  101.17  5609.4  101.56  5613.8   101.6
BR U #Mann= 8
  4186.7     .99  4718.9      .1  4909.6     .04  4952.1     .04  5044.9     .04
  5102.5     .08  5288.9    .025  5558.9     .08
BR U Banks=4952.1,5044.9
BR D #Sta/Elev= 95
  4178.9  102.73  4186.7  102.76  4268.9  103.13  4286.7   102.3  4298.9  101.73
  4306.7  101.07  4318.9  100.03  4326.7   99.64  4328.9   99.53  4346.7   99.89
  4358.9  100.13  4376.7   99.77  4388.9   99.53  4418.9  101.03  4426.7  101.06
  4588.9  101.63  4636.7  100.77  4638.9  100.73  4676.7   98.84  4678.9   98.73
  4688.9   98.63  4696.7   99.12  4718.9  100.53  4736.7  100.22  4757.3   99.86
  4786.7   100.1  4798.3  100.19  4840.7  100.54  4881.4  100.53  4896.4  100.53
  4909.6  100.16  4939.7   99.31 4939.79   99.31  4939.9    99.3 4940.01    99.3
  4952.1   98.96 4957.21   97.42  4957.3   97.39  4979.2   90.78  4979.6   91.04
  4989.8   88.94  4993.1   88.26  4995.5   87.16  4997.3    85.5  5003.2      86
  5004.4   87.18  5005.9    88.6  5019.6   90.38  5026.7   93.16 5039.19   97.48
  5039.3   97.51  5044.9   99.45 5059.49   99.65  5059.6   99.65 5059.71   99.65
    5060   99.66  5065.3   99.73  5092.9  100.27  5102.5  100.23    5136  100.09
  5206.7    99.8  5218.2   99.75  5236.7   99.29  5238.9   99.23  5276.7  100.46
  5278.9  100.53  5288.9  100.63  5296.7  100.24  5298.9  100.13  5308.9   99.23
  5316.7   98.14  5318.9   97.83  5326.1   96.21  5326.7   96.07  5336.7   93.82
  5338.9   93.33  5346.7   92.08  5348.9   91.73  5456.7   91.34  5458.9   91.33
  5466.7   92.03  5468.9   92.23  5476.7   93.56  5478.9   93.93    5486   95.56
  5486.7   95.72  5488.9   96.23  5506.7   98.54  5508.9   98.83  5516.7   99.33
  5526.7   99.97  5558.9  102.03  5566.7   102.1  5609.4  102.49  5613.8  102.53
BR D #Mann= 8
  4178.9     .99  4718.9      .1  4909.6     .04  4952.1     .04  5044.9     .04
  5102.5     .08  5288.9    .025  5558.9     .08
BR D Banks=4952.1,5044.9
BC Design=,, 0 ,, 0 ,,,,,,
BC HTab HWMax=102.25

Type RM Length L Ch R = 1 ,2887.8  ,102.4,106.6,106.1
BEGIN DESCRIPTION:
Woodwind Lane - 2
Detention pond on right VRR
END DESCRIPTION:
XS GIS Cut Line= 2
 3067889.555685213886457.1524229      3066548.91     13886343.69
#Sta/Elev= 30
  4268.9  103.06  4328.9   99.46  4358.9  100.06  4388.9   99.46  4418.9  100.96
  4588.9  101.56  4638.9  100.66  4688.9   98.56  4718.9  100.46  4757.3   99.79
  4909.6  100.09  4952.1   98.89  4979.2   90.71  4993.1   88.19  4997.3   85.43
  5003.2   85.93  5005.9   88.53  5019.6   90.31  5044.9   99.38  5102.5  100.16
  5238.9   99.16  5288.9  100.56  5318.9   97.76  5348.9   91.66  5458.9   91.26
  5468.9   92.16  5488.9   96.16  5508.9   98.76  5558.9  101.96  5613.8  102.46
#Mann= 8 ,-1 , 0
  4268.9     .99       0  4718.9      .1       0  4909.6     .04       0
  4952.1     .04       0  5044.9     .04       0  5102.5     .08       0
  5288.9    .025       0  5558.9     .08       0
#XS Ineff= 2 , 0
       0    4948   97.75    5050       0   97.75
Permanent Ineff=
       F       F
#Block Obstruct= 2 , 0
       0                  5288.8       0  100.55
Bank Sta=4952.1,5044.9
XS Rating Curve= 0
Exp/Cntr=.5,.3

Type RM Length L Ch R = 1 ,2781.2  ,240.6,246.1,252.2
BEGIN DESCRIPTION:
Woodwind Lane - 1
Interpolated channel, LIDAR overbanks
END DESCRIPTION:
XS GIS Cut Line= 2
      3067985.55      13886367.5      3066525.83     13886244.05
#Sta/Elev= 30
  4143.3   89.57  4173.3   90.48  4293.3   90.61  4353.3   89.79  4383.3   91.75
  4393.3   93.49  4413.3   94.76  4463.3   94.21  4493.3   90.78  4513.3   89.49
  4543.3   89.22  4573.3   89.72  4613.3   94.88  4663.3   97.53  4713.3   97.54
  4763.3   98.94 4955.55   98.22  4972.2   92.11 4994.46   86.77 4998.45   84.73
 5005.19   86.63 5008.27   88.93 5020.43   92.15  5046.3    97.3 5046.42   97.32
  5183.3   98.51  5433.3   98.54  5493.3   99.66  5513.3  100.65  5608.2  101.22
#Mann= 4 ,-1 , 0
  4143.3    .025       0  4763.3     .08       0 4955.55     .04       0
  5046.3     .08       0
#Block Obstruct= 2 , 0
       0  4763.3    98.9               0
Bank Sta=4955.55,5046.42
XS Rating Curve= 0
Exp/Cntr=.3,.1

Type RM Length L Ch R = 1 ,2535.1  ,1038.4,1027.5,983.7
BEGIN DESCRIPTION:
Cross Section Xsec3
Located At: DS WOODWIND LANE
END DESCRIPTION:
XS GIS Cut Line= 2
 3067802.578654213886128.6335886      3066488.41     13886010.36
#Sta/Elev= 30
  4302.4    99.8  4372.4    98.2  4622.4    98.8  4652.4    97.7  4672.4    96.6
  4702.4    96.5  4722.4    97.6  4842.4    98.1    4873   97.39  4942.4    96.6
  4960.7   96.47  4963.5   96.66  4978.1   88.69  4993.4   85.21  4997.2   83.52
  5001.1   83.13  5002.7   83.77  5009.2      88  5020.5    92.6  5029.4   97.32
  5071.1   96.97    5077   97.38  5087.3   98.09  5152.4    96.5  5192.4    97.2
  5202.4    97.6  5412.4      99  5472.4    98.3  5522.4   100.5  5621.9   100.9
#Mann= 6 ,-1 , 0
  4302.4     .99       0  4842.4      .1       0  4963.5     .08       0
  5029.4      .1       0    5077     .08       0  5621.9      .2       0
Bank Sta=4963.5,5071.1
XS Rating Curve= 0
Exp/Cntr=.3,.1

Type RM Length L Ch R = 1 ,1507.6  ,393.8,407.1,408
BEGIN DESCRIPTION:
Cross Section Xsec2.0
Located At: 2ND US LAKE DR
END DESCRIPTION:
XS GIS Cut Line= 4
      3067890.06     13885479.72      3066897.66     13884999.76
      3066511.74     13885310.36      3066255.31     13885775.63
#Sta/Elev= 30
  3616.2   100.5  3616.3   100.5  3806.2    99.1  3896.2    99.1  4016.2    97.7
  4376.2    96.9  4426.2    97.9  4516.3   97.37  4666.2    96.5  4706.2    97.1
  4853.4   96.61  4878.6    95.6  4898.6    95.5  4918.6    94.5  4971.6   94.16
  4979.4   93.47  4987.8   86.29  4997.8   80.43  4998.4   79.54  4999.6   79.32
  5001.5   79.56  5008.1   85.23  5013.1   85.85  5024.4   93.82  5031.7   94.63
  5074.3   95.03  5188.6    96.1    5294    96.5    5314    95.9  5745.2   101.1
#Mann= 8 ,-1 , 0
  3616.2      .2       0  3616.3     .08       0  4516.3     .12       0
  4853.4     .08       0  4971.6     .08       0  5024.4     .08       0
  5074.3     .12       0    5294     .08       0
Bank Sta=4971.6,5024.4
XS Rating Curve= 0
Exp/Cntr=.3,.1

Type RM Length L Ch R = 1 ,1100.5  ,516.4,541.8,550.4
BEGIN DESCRIPTION:
Cross Section Xsec1.0
Located At: US LAKE DR
END DESCRIPTION:
XS GIS Cut Line= 4
      3067616.03      13884964.4      3066971.26     13884606.05
      3066376.72     13884882.19       3065994.6     13885634.56
#Sta/Elev= 30
  3831.2    97.8  4091.2    96.4  4111.2    95.9  4151.2    96.6  4427.7   96.27
  4568.9    96.1  4748.9    97.1  4788.9      96  4918.9    95.4  4949.7   93.75
  4971.8   94.98  4977.3   94.43  4986.4   85.81  4991.5   83.85  4996.2   79.77
  4996.7   78.76  5000.4   78.44  5003.4   79.08  5003.8   79.72  5012.3   86.94
  5021.3   93.99  5039.1   93.47  5095.9   93.95  5198.9    94.3  5224.4      94
  5674.4    95.2  5714.4    96.1  5784.4    95.9  6044.4    99.3  6068.2    99.9
#Mann= 7 ,-1 , 0
  3831.2     .08       0  4427.7     .12       0  4949.7      .1       0
  4977.3     .08       0  5021.3      .1       0  5095.9     .12       0
  5224.4     .08       0
Bank Sta=4977.3,5021.3
XS Rating Curve= 0
Exp/Cntr=.3,.1

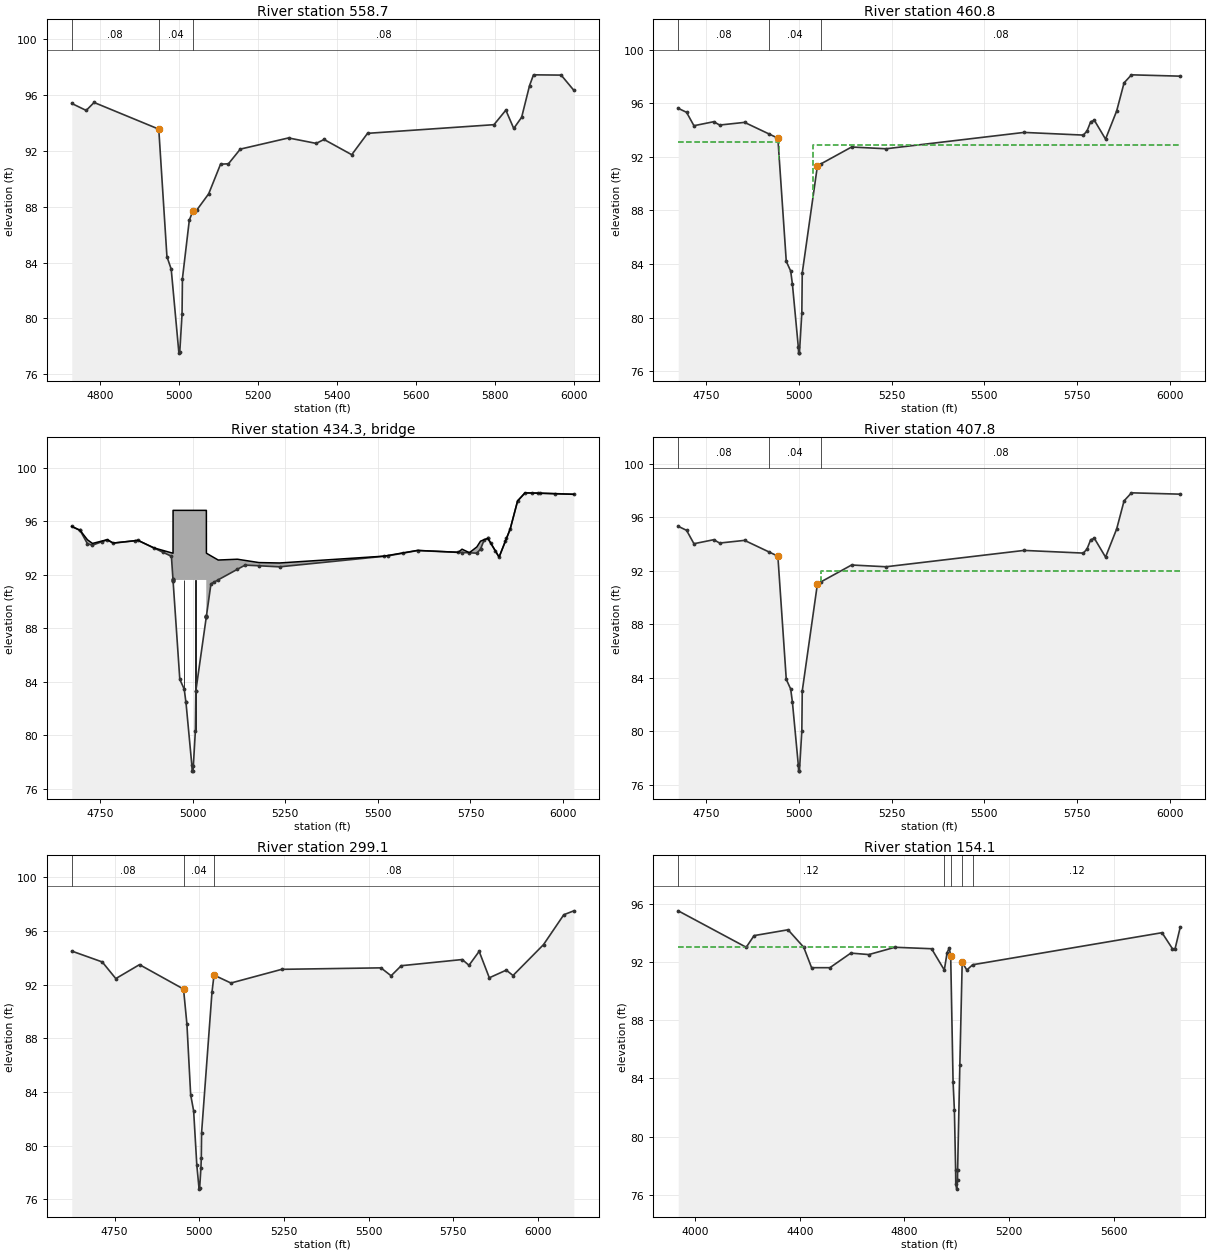
Type RM Length L Ch R = 1 ,558.7   ,97.5,97.9,101.6
BEGIN DESCRIPTION:
Lake Drive - 4
Interpolated channel, LIDAR overbanks
END DESCRIPTION:
XS GIS Cut Line= 4
      3066686.69      13884298.3      3066653.32     13884283.44
      3066221.31     13884282.63      3065475.87      13884578.7
#Sta/Elev= 30
  4727.9   95.39  4764.4   94.89  4784.4   95.46 4948.08   93.55 4968.74   84.42
 4979.57   83.52 4999.04   77.51 5001.14   77.57 5006.96   80.29 5007.96   82.85
 5025.36   87.03  5034.4   87.69  5044.4   87.76  5074.4   88.92  5104.4   91.04
  5124.4   91.07  5154.4   92.12  5276.4   92.92  5346.4   92.53  5366.4   92.81
  5436.4   91.72  5476.4   93.25  5796.4   93.87  5826.4   94.91  5846.4    93.6
  5866.4    94.4  5886.4   96.67  5896.4   97.44  5966.4   97.42  5998.5   96.33
#Mann= 3 ,-1 , 0
  4727.9     .08       0 4948.08     .04       0  5034.4     .08       0
Bank Sta=4948.08,5034.4
XS Rating Curve= 0
Exp/Cntr=.5,.3

Type RM Length L Ch R = 1 ,460.8   ,55,53,52.9
BEGIN DESCRIPTION:
Lake Drive - 3
END DESCRIPTION:
XS GIS Cut Line= 4
      3066727.38     13884206.96      3066674.68     13884183.48
      3066202.27      13884182.6      3065438.96     13884485.76
#Sta/Elev= 30
  4673.9   95.62  4696.4   95.32  4716.3   94.32  4769.8   94.62  4785.6   94.37
  4852.9   94.57  4919.3    93.7  4942.8   93.39  4965.5   84.19  4977.4   83.47
 4982.11   82.48    4998   77.79  4998.8   77.34  5001.1   77.38  5007.5   80.36
  5008.6   83.32  5049.6   91.33    5059   91.47  5141.8   92.73  5234.7    92.6
  5607.2   93.82  5767.2   93.62  5777.1   93.92  5787.2   94.62  5797.1   94.72
  5827.2   93.32  5857.2   95.42  5877.2   97.52  5897.2   98.12    6029   98.02
#Mann= 3 ,-1 , 0
  4673.9     .08       0  4919.3     .04       0    5059     .08       0
#XS Ineff= 2 , 0
       0  4946.9   93.08  5037.2       0   92.85
Permanent Ineff=
       F       F
Bank Sta=4942.8,5049.6
XS Rating Curve= 0
Exp/Cntr=.5,.3

Type RM Length L Ch R = 3 ,434.3   ,,,
BEGIN DESCRIPTION:
LAKE DRIVE
Structure ID: E125-00-00-01
END DESCRIPTION:
Bridge Culvert--1,0,-1,-1, 0
Deck Dist Width WeirC Skew NumUp NumDn MinLoCord MaxHiCord MaxSubmerge Is_Ogee
10,33,2.6,0, 35, 35, , , .95, 0, ,,,
  4673.9  4696.4  4716.3  4729.8  4769.8  4785.6  4852.9  4895.5  4942.8  4947.2
  4947.3 5036.89    5037  5037.2  5037.3  5049.6  5069.1  5121.1  5141.8  5179.1
  5234.7  5516.4  5607.2  5717.2  5727.2  5747.2  5767.2  5777.1  5787.2  5797.1
  5827.2  5857.2  5877.2  5897.2    6029
    95.6   95.31    94.6   94.33   94.61   94.36   94.56      94   93.63    93.6
    96.8    96.8    96.8    96.8    93.6    93.4   93.09   93.15   93.06    92.9
   92.87   93.38   93.81   93.67    93.9   93.64   94.07    94.5   94.61   94.71
   93.31   95.41   97.51   98.11      98
    95.6    95.3    94.3    94.2    94.6   94.35   94.55   93.99   93.37    91.6
    91.6    91.6   88.84   88.88    88.9   91.31   91.61    92.4   92.71   92.66
   92.58   93.37    93.8   93.66   93.65   93.63    93.6    93.9    94.6    94.7
    93.3    95.4    97.5    98.1      98
  4673.9  4696.4  4716.3  4729.8  4769.8  4785.6  4852.9  4895.5  4942.8  4947.2
  4947.3 5036.89    5037  5037.2  5037.3  5049.6  5069.1  5121.1  5141.8  5179.1
  5234.7  5516.4  5607.2  5717.2  5727.2  5747.2  5767.2  5777.1  5787.2  5797.1
  5827.2  5857.2  5877.2  5897.2    6029
    95.6   95.31    94.6   94.33   94.61   94.36   94.56      94   93.63    93.6
    96.8    96.8    96.8    96.8    93.6    93.4   93.09   93.15   93.06    92.9
   92.87   93.38   93.81   93.67    93.9   93.64   94.07    94.5   94.61   94.71
   93.31   95.41   97.51   98.11      98
   95.34   95.04   94.04   93.94   94.34   94.09   94.29   93.73   93.11   91.34
   91.34   91.34   88.58   88.62   88.64   91.05   91.35   92.14   92.45    92.4
   92.32   93.11   93.54    93.4   93.39   93.37   93.34   93.64   94.34   94.44
   93.04   95.14   97.24   97.84   97.74
Pier Skew, UpSta & Num, DnSta & Num=  ,4977.4, 2 ,4977.4, 2 , 0 , 0 , 0 ,,
     1.2     1.2
   82.32    92.6
     1.2     1.2
   82.06   92.34
Pier Skew, UpSta & Num, DnSta & Num=  ,5007.5, 2 ,5007.5, 2 , 0 , 0 , 0 ,,
     1.2     1.2
   79.05    92.6
     1.2     1.2
   78.79   92.34
BR Coef= 1 , 1 , 1 ,1.25, 0 ,,,.8,0,2,0,
WSPro=,,,, 1 ,,,, 0 ,,,, 0 ,,,,-1 ,-1 ,-1 , 0 , 0 , 0 , 0 , 0
BR U #Sta/Elev= 69
  4673.9    95.6  4696.3    95.3  4696.4    95.3  4716.3    94.3  4729.8    94.2
  4756.4   94.47  4769.8    94.6  4785.6   94.35  4844.6   94.53  4852.9   94.55
  4895.5   93.99  4919.3   93.68  4942.8   93.37 4946.91    91.7    4947   91.67
 4947.09   91.63  4947.2   91.59  4947.3   91.55 4947.41    91.5  4965.5   84.17
  4977.4   83.45    4982   82.46 4982.11   82.46    4998   77.77  4998.8   77.32
  5001.1   77.36    5002   77.69  5007.5   80.34  5008.6    83.3 5008.71    83.3
 5036.89   88.82    5037   88.84 5037.09   88.86  5037.2   88.88  5037.3    88.9
 5037.41   88.92  5049.6   91.31    5059   91.45  5069.1   91.61  5121.1    92.4
  5141.8   92.71  5179.1   92.66  5234.7   92.58  5516.4   93.37  5527.2    93.4
  5567.2    93.6  5607.2    93.8  5717.2   93.66  5727.2   93.65  5747.2   93.63
  5767.2    93.6  5777.1    93.9  5777.2   93.91  5787.2    94.6  5797.1    94.7
  5797.2    94.7  5804.9   94.34  5817.2   93.77  5827.2    93.3    5844   94.48
  5847.2    94.7  5857.2    95.4  5877.2    97.5  5897.2    98.1  5917.2    98.1
  5931.7    98.1  5937.2   98.09  5977.2   98.05    6029      98
BR U #Mann= 5
  4673.9     .08  4919.3     .04  4942.8     .04  5049.6     .04    5059     .08
BR U Banks=4942.8,5049.6
BR D #Sta/Elev= 69
  4673.9   95.34  4696.3   95.04  4696.4   95.04  4716.3   94.04  4729.8   93.94
  4756.4   94.21  4769.8   94.34  4785.6   94.09  4844.6   94.27  4852.9   94.29
  4895.5   93.73  4919.3   93.42  4942.8   93.11 4946.91   91.44    4947   91.41
 4947.09   91.37  4947.2   91.33  4947.3   91.29 4947.41   91.24  4965.5   83.91
  4977.4   83.19    4982    82.2 4982.11    82.2    4998   77.51  4998.8   77.06
  5001.1    77.1    5002   77.43  5007.5   80.08  5008.6   83.04 5008.71   83.04
 5036.89   88.56    5037   88.58 5037.09    88.6  5037.2   88.62  5037.3   88.64
 5037.41   88.66  5049.6   91.05    5059   91.19  5069.1   91.35  5121.1   92.14
  5141.8   92.45  5179.1    92.4  5234.7   92.32  5516.4   93.11  5527.2   93.14
  5567.2   93.34  5607.2   93.54  5717.2    93.4  5727.2   93.39  5747.2   93.37
  5767.2   93.34  5777.1   93.64  5777.2   93.65  5787.2   94.34  5797.1   94.44
  5797.2   94.44  5804.9   94.08  5817.2   93.51  5827.2   93.04    5844   94.22
  5847.2   94.44  5857.2   95.14  5877.2   97.24  5897.2   97.84  5917.2   97.84
  5931.7   97.84  5937.2   97.83  5977.2   97.79    6029   97.74
BR D #Mann= 5
  4673.9     .08  4919.3     .04  4942.8     .04  5049.6     .04    5059     .08
BR D Banks=4942.8,5049.6
BC Design=,, 0 ,, 0 ,,,,,,
BC HTab HWMax=98.12

Type RM Length L Ch R = 1 ,407.8   ,100.1,108.7,110
BEGIN DESCRIPTION:
Lake Drive - 2
END DESCRIPTION:
XS GIS Cut Line= 4
      3066749.04     13884166.36      3066671.78     13884127.75
      3066202.27     13884128.46      3065425.42     13884447.86
#Sta/Elev= 30
  4673.9   95.32  4696.4   95.02  4716.3   94.02  4769.8   94.32  4785.6   94.07
  4852.9   94.27  4919.3    93.4  4942.8   93.09  4965.5   83.89  4977.4   83.17
 4982.11   82.18    4998   77.49  4998.8   77.04  5001.1   77.08  5007.5   80.06
  5008.6   83.02  5049.6   91.03    5059   91.17  5141.8   92.43  5234.7    92.3
  5607.2   93.52  5767.2   93.32  5777.1   93.62  5787.2   94.32  5797.1   94.42
  5827.2   93.02  5857.2   95.12  5877.2   97.22  5897.2   97.82    6029   97.72
#Mann= 3 ,-1 , 0
  4673.9     .08       0  4919.3     .04       0    5059     .08       0
#XS Ineff= 2 , 0
       0    4932      92    5059       0      92
Permanent Ineff=
       F       F
Bank Sta=4942.8,5049.6
XS Rating Curve= 0
Exp/Cntr=.5,.3

Type RM Length L Ch R = 1 ,299.1   ,142.4,145,144.4
BEGIN DESCRIPTION:
Lake Drive - 1
Interpolated channel, LIDAR overbanks
END DESCRIPTION:
XS GIS Cut Line= 4
      3066793.74      13884076.9      3066695.31     13884027.71
      3066182.44     13884028.49       3065387.4     13884355.38
#Sta/Elev= 30
  4623.5   94.51  4713.5    93.7  4753.5   92.46  4823.5    93.5  4953.5   91.68
  4963.5   89.07 4974.57    83.8 4983.34    82.6 4992.77   78.54 4999.49   76.77
 5001.21   76.88 5004.94   78.38 5005.99   79.11 5006.81   80.97 5037.47   91.43
  5043.5   92.72  5093.5   92.13  5243.5   93.15  5536.4   93.26  5566.4   92.67
  5596.4   93.42  5776.4   93.88  5796.4   93.45  5826.4   94.49  5856.4   92.52
  5906.4   93.09  5926.4   92.69  6016.4   94.99  6076.4   97.22    6106   97.51
#Mann= 3 ,-1 , 0
  4623.5     .08       0  4953.5     .04       0  5043.5     .08       0
Bank Sta=4953.5,5043.5
XS Rating Curve= 0
Exp/Cntr=.3,.1

Type RM Length L Ch R = 1 ,154.1   ,0,0,0
BEGIN DESCRIPTION:
Cross Section Xsec1a
END DESCRIPTION:
XS GIS Cut Line= 4
      3067444.68     13884217.79      3066794.41      13883887.3
      3066250.99     13883887.56      3065641.96      13884104.1
#Sta/Elev= 30
  3935.3    95.5  4195.3      93  4225.3    93.8  4355.3    94.2  4415.3      93
  4445.3    91.6  4515.3    91.6  4595.3    92.6  4664.2    92.5  4764.2      93
  4904.2    92.9  4952.9   91.44  4963.6   92.63  4971.8   92.95  4977.3    92.4
  4986.4   83.78  4991.5   81.82  4996.2   77.74  4996.7   76.73  5000.4   76.41
  5003.4   77.05  5003.8   77.69  5012.3   84.91  5021.3   91.96  5039.1   91.44
  5061.1    91.8  5785.5      94  5825.5    92.9  5835.5    92.9  5855.5    94.4
#Mann= 5 ,-1 , 0
  3935.3     .12       0  4952.9     .04       0  4977.3     .04       0
  5021.3     .04       0  5061.1     .12       0
#XS Ineff= 2 , 0
       0 4764.16      93               0
Permanent Ineff=
       F       F
Bank Sta=4977.3,5021.3
XS Rating Curve= 0
Exp/Cntr=.3,.1

Chan Stop Cuts=-1